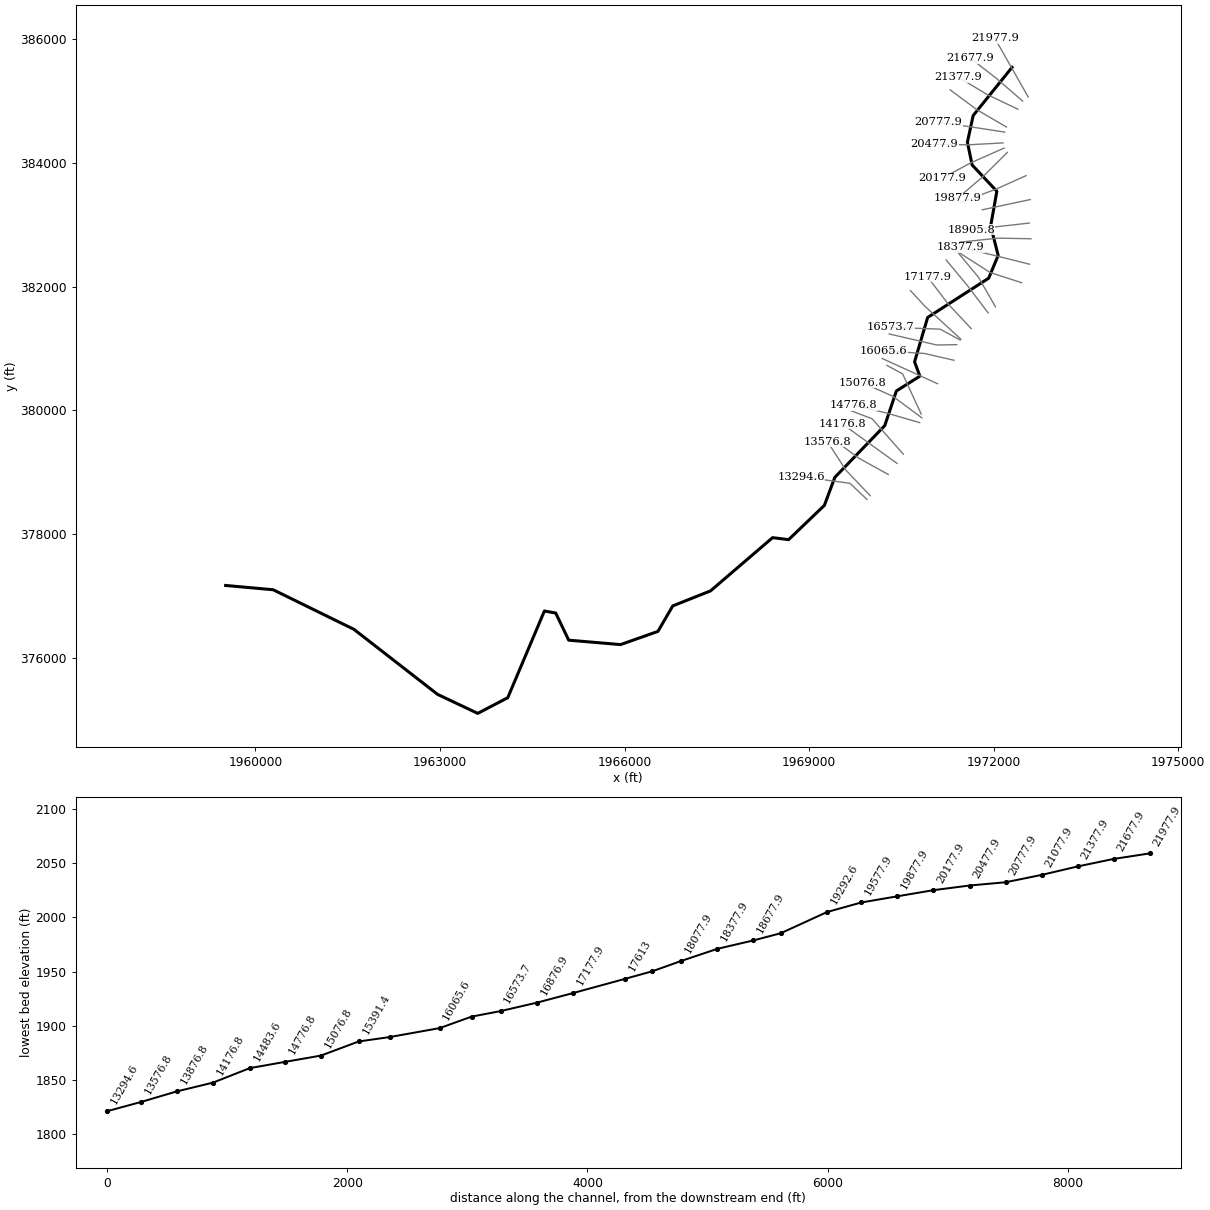
--- KeeneyCrk.prj (project) ---

Proj Title=KeeneyCrk
Current Plan=p01
Default Exp/Contr=0,0
English Units
Geom File=g01
Flow File=f01
Plan File=p01
BEGIN DESCRIPTION:
END DESCRIPTION:
DSS Export Rating Curves= 0
DSS Export Rating Curve Sorted= 0
DSS Export Volume Flow Curves= 0
DXF OffsetX= 0
DXF OffsetY= 0
DXF ScaleX= 0
DXF ScaleY= 0

--- KeeneyCrk.p01 (plan) ---

Plan Title=Floodplain
Program Version=4.00
Geom File=g01
Flow File=f01
K Sum by GR=0
Std Step Tol=0.01
Critical Tol=0.01
Num of Std Step Trials=20
Max Error Tol=0.3
Flow Tol Ratio=0.001
Split Flow NTrial=30
Split Flow Tol=0.02
Split Flow Ratio=0.02
Log Output Level=0
Friction Slope Method=1
Unsteady Friction Slope Method=2
Unsteady Bridges Friction Slope Method=1
Global Log Level=0
CheckData=False
Run HTab=0
Run UNet=0
Run PostProcess=0
UNET Theta=0
UNET Theta Warmup=0
UNET ZTol=0
UNET ZSATol=0
UNET MxIter=0
UNET MaxInSteps=0
UNET DtIC=0
UNET DtMin=0
UNET MaxCRTS=0
UNET WFStab=0
UNET SFStab=0
UNET WFX=0
UNET SFX=0
UNET DSS MLevel=0
UNET DZMax Abort=0
UNET Convert EG Bridges=0
UNET Use Existing IB Tables=0
UNET Froude Limit=0
UNET Froude Power=0
Write IC File=0
Echo Input=False
Echo Output=False
Write Detailed=0

--- KeeneyCrk.f01 (steady flow) ---

Flow Title=NFF Regression Equation
Program Version=4.00
Number of Profiles=1
Profile Names=P100yr
River Rch & RM=KeeneyCrk,Main      ,21977.9
546.8267
River Rch & RM=KeeneyCrk,Main      ,19577.9
582.1193
River Rch & RM=KeeneyCrk,Main      ,19292.6
650.2291
River Rch & RM=KeeneyCrk,Main      ,18077.9
660.3861
River Rch & RM=KeeneyCrk,Main      ,17837.3
812.2956
River Rch & RM=KeeneyCrk,Main      ,15651.2
864.4113
River Rch & RM=KeeneyCrk,Main      ,15391.4
963.4635
River Rch & RM=KeeneyCrk,Main      ,13294.6
1021.841
River Rch & RM=KeeneyCrk,Main      ,12178
1134.597
River Rch & RM=KeeneyCrk,Main      ,9976.6
1166.504
River Rch & RM=KeeneyCrk,Main      ,7169.1
1292.921
River Rch & RM=KeeneyCrk,Main      ,6658.3
1519.864
River Rch & RM=KeeneyCrk,Main      ,4869.5
1590.264
Boundary for River Rch & Prof#=KeeneyCrk,Main      ,1
Up Type=0
Dn Type=3
Dn Slope=0.1284

--- KeeneyCrk.g01 (geometry) ---

Geom Title=USGS 3m DEM
Program Version=4.10

River Reach=KeeneyCrk       ,Main
Reach XY= 30
     1972299.095      385548.768     1971667.151      384769.254
     1971573.401      384338.699      1971649.79      383968.907
     1972052.035      383543.722     1971951.873      382982.796
     1972073.401      382505.366     1971918.887       382137.31
     1970927.213      381501.991     1970714.524      380784.155
     1970800.831      380552.241     1970418.887      380312.657
     1970229.651      379751.893     1969417.834      378914.036
     1969248.748      378461.963     1968667.651      377907.353
     1968406.734      377939.393     1967398.053      377078.282
     1966784.425      376835.368     1966543.325      376422.914
     1965935.686      376209.372     1965092.975      376280.862
     1964881.867      376719.788     1964697.839      376752.774
     1964102.353      375349.997     1963614.506      375096.524
     1962962.924      375403.202     1961602.353        376455.9
     1960289.853      377096.524     1959516.896      377166.105

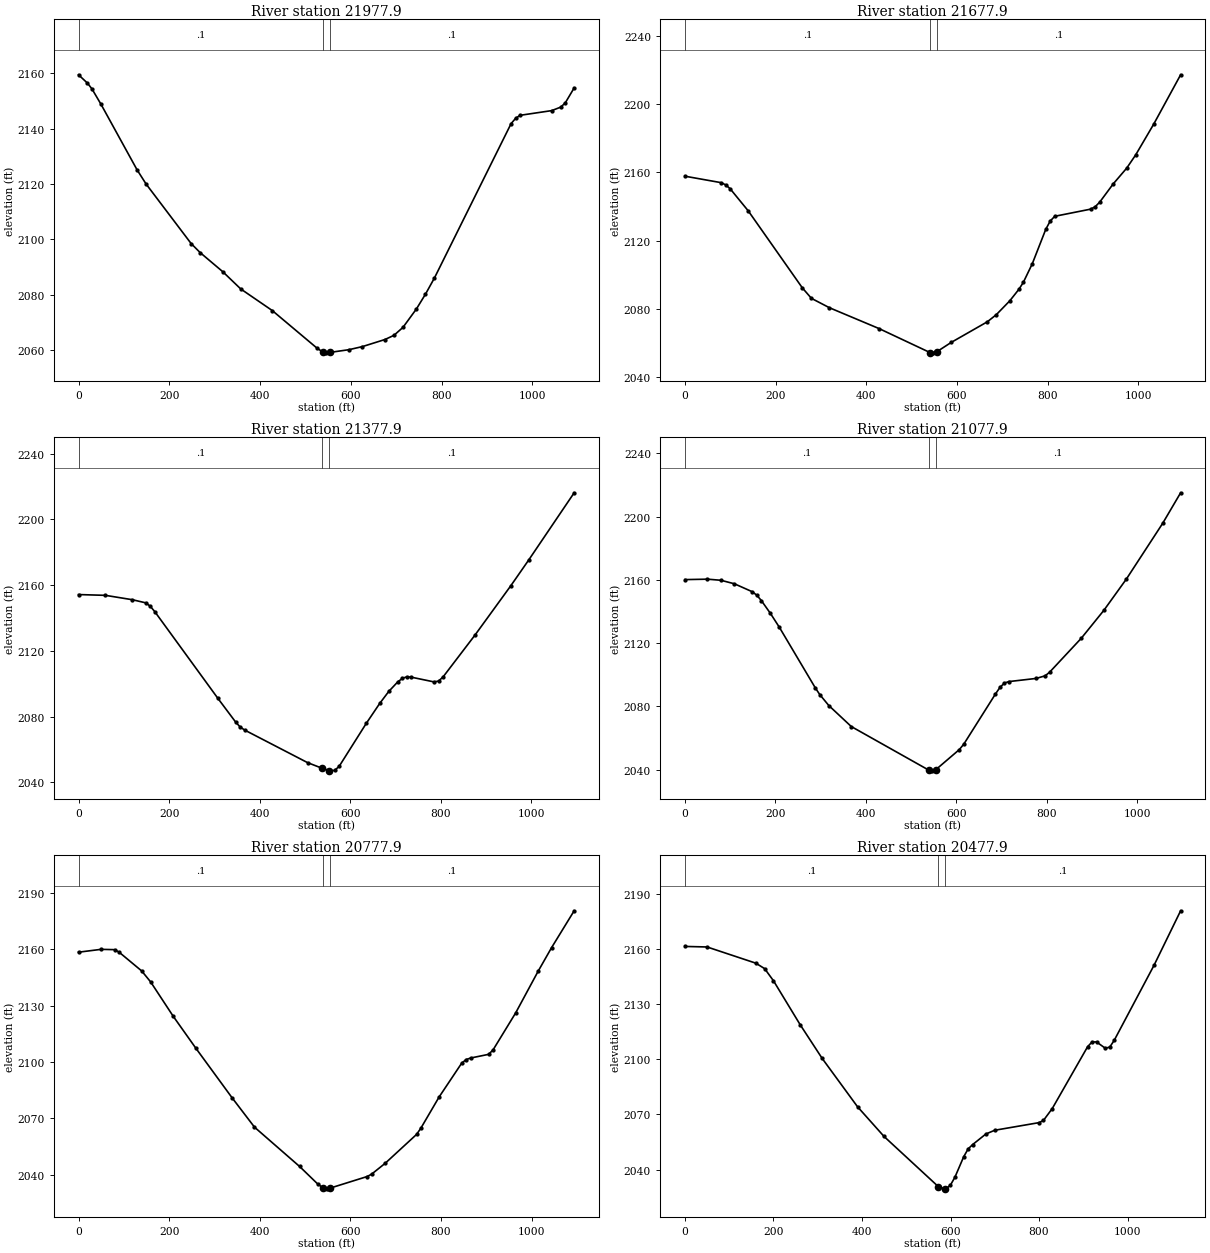
Type RM Length L Ch R = 1 ,21977.9 ,292.3,300,308.8
XS GIS Cut Line= 3
     1972561.304      385069.746     1972290.413      385543.807
     1972019.521      386017.868
#Sta/Elev= 30
       0 2159.42    19.8 2156.39    29.8 2154.28    49.6 2148.76     129 2125.13
   148.9 2120.01   248.2 2098.52     268 2095.27   317.7  2088.4   357.4 2082.16
   426.9 2074.36   526.2  2060.7   538.5 2059.39     546 2059.11   553.5 2059.26
   595.6 2060.24   625.4 2061.36     675 2063.91   694.9 2065.42   714.8 2068.29
   744.6 2074.98   764.4 2080.27   784.2 2086.13     953 2141.79     963 2143.71
   972.9  2144.8  1042.4 2146.49  1062.2 2147.74  1072.2 2149.23    1092 2154.69
#Mann= 3 , 0 , 0
       0      .1       0   538.5    .045       0   553.5      .1       0
Bank Sta=538.5,553.5
XS Rating Curve= 0 ,0
Exp/Cntr=0.3,0.1

Type RM Length L Ch R = 1 ,21677.9 ,294,300,302.7
XS GIS Cut Line= 3
     1972471.154       385003.16     1972056.058      385360.926
     1971624.876      385695.312
#Sta/Elev= 30
       0 2157.82    79.7 2154.03    89.7 2152.75    99.6 2150.47   139.5 2137.48
     259 2092.17     279 2086.03   318.8 2080.51   428.4 2068.25   540.5  2054.2
     548 2054.01   555.5 2054.63   587.7 2060.18     667 2072.24   686.9 2076.43
   716.6 2084.57   736.5 2091.26   746.4 2095.36   766.3 2106.37     796 2126.58
   805.9  2131.5   815.9 2134.26   895.2 2138.47   905.2 2139.91   915.1 2142.59
   944.8 2153.28   974.6 2162.56   994.4 2170.33  1034.1 2188.37  1093.6 2217.43
#Mann= 3 , 0 , 0
       0      .1       0   540.5    .045       0   555.5      .1       0
Bank Sta=540.5,555.5
XS Rating Curve= 0 ,0
Exp/Cntr=0.3,0.1

Type RM Length L Ch R = 1 ,21377.9 ,301.8,299.8,297.6
XS GIS Cut Line= 3
     1972393.833      384871.494     1971900.997      385105.274
     1971429.471      385386.432
#Sta/Elev= 30
       0 2154.26    59.5 2153.78     119 2151.12   148.8  2149.2   158.7 2147.07
   168.6 2143.81   307.4 2091.28   347.1 2076.68     357 2073.72     367 2071.85
   505.8 2052.06     538 2048.63     553 2047.26   555.4 2047.07   565.4 2047.33
   575.4 2049.74   635.3 2075.88   665.2 2088.09   685.2 2095.39   705.2 2101.23
   715.2 2103.31   725.1 2104.26   735.1 2104.01     785 2101.15     795 2101.65
     805 2104.17   874.9  2129.4   954.7 2159.66   994.6 2175.47  1094.5 2216.15
#Mann= 3 , 0 , 0
       0      .1       0     538    .045       0     553      .1       0
Bank Sta=538,553
XS Rating Curve= 0 ,0
Exp/Cntr=0.3,0.1

Type RM Length L Ch R = 1 ,21077.9 ,291.4,300,311.2
XS GIS Cut Line= 3
     1972207.666      384583.423      1971735.01       384858.01
     1971292.858      385184.088
#Sta/Elev= 30
       0 2160.16    49.7 2160.44    79.5 2159.74   109.3 2157.52   149.1 2152.46
     159 2150.24     169 2146.86   188.8 2138.86   208.7 2130.02   288.2  2091.7
   298.2 2087.42     318 2080.56   367.7 2067.28   539.1 2039.71   546.6 2039.26
   554.1 2039.86   606.6 2052.69   616.6 2056.16   686.5 2087.84   696.5 2092.01
   706.4 2094.79   716.4  2095.7   776.4 2097.68   796.4 2099.33   806.3 2101.63
   876.3 2123.08   926.2 2140.72   976.2 2160.59  1056.1 2195.65    1096 2215.06
#Mann= 3 , 0 , 0
       0      .1       0   539.1    .045       0   554.1      .1       0
Bank Sta=539.1,554.1
XS Rating Curve= 0 ,0
Exp/Cntr=0.3,0.1

Type RM Length L Ch R = 1 ,20777.9 ,295.2,299.9,302.5
XS GIS Cut Line= 3
     1972179.057       384501.01       1971637.7      384584.107
     1971096.869      384660.293
#Sta/Elev= 30
       0 2158.53    49.8 2160.05    79.7 2159.88    89.6 2158.54   139.4 2148.55
   159.3 2142.67   209.1 2124.37   258.9 2107.41   338.6 2081.09   388.4 2065.34
     488 2044.39   527.8  2035.1   540.2 2032.91   547.7 2032.49   555.2 2032.87
   637.1 2039.05     647 2040.34   676.8 2046.09   746.3 2061.53   756.2 2065.06
     796 2081.48   845.6  2099.4   855.5 2101.36   865.5 2102.17   905.2 2104.13
   915.1 2106.57   964.8  2126.2  1014.4  2148.4  1044.2 2161.02  1093.9 2180.59
#Mann= 3 , 0 , 0
       0      .1       0   540.2    .045       0   555.2      .1       0
Bank Sta=540.2,555.2
XS Rating Curve= 0 ,0
Exp/Cntr=0.3,0.1

Type RM Length L Ch R = 1 ,20477.9 ,291.8,300,311.6
XS GIS Cut Line= 3
     1972152.228      384326.293     1971573.227      384294.256
     1971033.318      384307.762
#Sta/Elev= 30
       0 2161.29      50    2161     160  2152.2     180 2149.22     200 2142.61
     260 2118.84   309.9 2100.44   389.9 2074.12   449.9 2057.95   572.4 2030.72
   587.4  2029.5   589.9 2029.49   599.9 2031.53   609.9 2035.78   629.9 2046.99
   639.9 2051.22   649.9 2053.54   679.9 2059.31   699.9 2061.34   799.9 2065.48
   809.9 2066.65   829.9 2073.14   909.9 2106.81   919.9 2109.37   929.9 2109.37
   949.9 2105.92   959.9 2106.58   969.9 2110.23    1060 2151.09    1120 2180.68
#Mann= 3 , 0 , 0
       0      .1       0   572.4    .045       0   587.4      .1       0
Bank Sta=572.4,587.4
XS Rating Curve= 0 ,0
Exp/Cntr=0.3,0.1

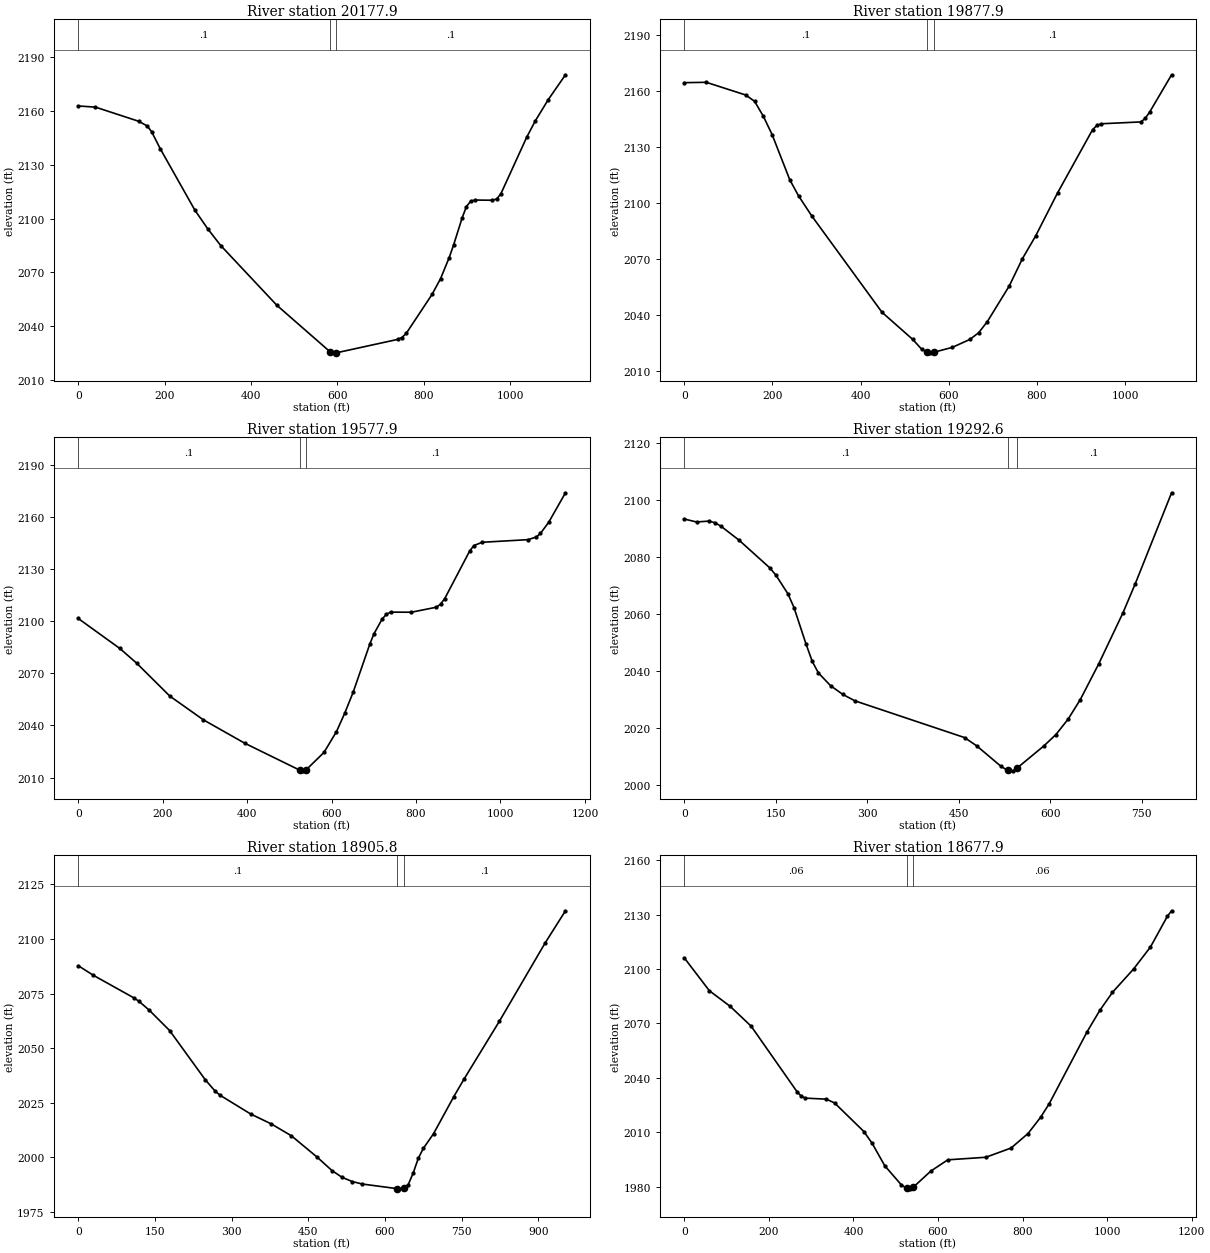
Type RM Length L Ch R = 1 ,20177.9 ,291.8,300,304.7
XS GIS Cut Line= 3
     1972170.563      384242.222     1971630.573       384004.72
     1971156.288      383750.225
#Sta/Elev= 30
       0 2162.72      40 2162.06     140 2154.19     160 2151.54     170 2148.34
     190 2138.86     270 2104.73     300 2094.24     330 2084.97   459.9  2051.7
   582.4 2025.94   597.4  2025.2   739.4 2032.67   749.4 2033.72   759.4 2036.01
   819.2 2057.72   839.1 2066.59     859  2078.3     869 2085.18   888.9 2100.35
   898.9 2106.71   908.9 2109.72   918.8 2110.31   958.7  2110.2   968.7 2110.87
   978.6 2113.79  1038.4 2145.29  1058.4 2154.44  1088.3 2166.24  1128.2 2180.09
#Mann= 3 , 0 , 0
       0      .1       0   582.4    .045       0   597.4      .1       0
Bank Sta=582.4,597.4
XS Rating Curve= 0 ,0
Exp/Cntr=0.3,0.1

Type RM Length L Ch R = 1 ,19877.9 ,308.1,300,292.3
XS GIS Cut Line= 3
     1972223.318      384173.079     1971826.284      383780.906
      1971408.78       383426.83
#Sta/Elev= 30
       0 2164.28    49.8 2164.48   139.5 2157.65   159.4 2154.29   179.4 2146.23
   199.3 2136.39   239.2 2112.28   259.1 2103.66     289 2092.93   448.4 2041.29
   518.2 2026.74   538.1 2021.58   550.6 2019.84   558.1 2019.55   565.6 2019.84
   607.8 2022.46   647.6 2026.71   667.6 2030.27   687.5 2036.29   737.2 2055.38
   767.1 2070.02   796.9  2082.1   846.7 2105.19   926.3 2139.12   936.3 2141.43
   946.2 2142.27  1035.8 2143.26  1045.8 2145.19  1055.7 2148.53  1105.5 2168.51
#Mann= 3 , 0 , 0
       0      .1       0   550.6    .045       0   565.6      .1       0
Bank Sta=550.6,565.6
XS Rating Curve= 0 ,0
Exp/Cntr=0.3,0.1

Type RM Length L Ch R = 1 ,19577.9 ,290,285.3,281.9
XS GIS Cut Line= 3
     1972527.439      383796.517     1972041.157      383578.971
     1971459.599       383360.55
#Sta/Elev= 30
       0 2101.53    98.6 2084.25   138.1 2075.88     217 2056.85     296 2043.27
   394.6 2029.72   525.2 2014.18   532.7 2013.86   540.2 2014.56     582 2024.43
   611.6 2036.41   631.3 2047.07     651    2059   690.5 2086.72   700.4  2092.7
   720.1 2101.32   729.9 2103.89   739.8 2105.17   789.1 2105.12   848.3    2108
   858.1 2109.78     868 2112.95   927.2 2140.38     937 2143.47   956.7 2145.36
  1065.2 2146.87  1084.9 2148.39  1094.8 2150.46  1114.5 2156.97    1154 2173.84
#Mann= 3 , 0 , 0
       0      .1       0   525.2    .045       0   540.2      .1       0
Bank Sta=525.2,540.2
XS Rating Curve= 0 ,0
Exp/Cntr=0.3,0.1

Type RM Length L Ch R = 1 ,19292.6 ,388.6,386.5,384.4
XS GIS Cut Line= 2
      1972595.44      383409.631     1971813.968      383243.624
#Sta/Elev= 30
       0 2093.39      20 2092.36      40 2092.66    49.9 2092.12    59.9  2090.9
    89.9 2085.94   139.8 2076.32   149.8 2073.81   169.8 2067.18   179.8 2062.35
   199.7 2049.42   209.7 2043.48   219.7 2039.44   239.7 2034.94   259.6  2031.9
   279.6 2029.62   459.4 2016.73   479.4 2013.82   519.3 2006.62   530.1  2005.2
   539.3 2005.06   545.1 2005.95   589.2 2013.75   609.2 2017.77   629.1 2023.15
   649.1 2030.01   679.1 2042.44     719 2060.41     739 2070.52   798.9  2102.6
#Mann= 3 , 0 , 0
       0      .1       0   530.1    .045       0   545.1      .1       0
Bank Sta=530.1,545.1
XS Rating Curve= 0 ,0
Exp/Cntr=0.3,0.1

Type RM Length L Ch R = 1 ,18905.8 ,230.8,227.9,227.7
XS GIS Cut Line= 2
     1972579.599      383029.138     1971632.063      382923.253
#Sta/Elev= 30
       0 2087.76    29.8 2083.32   109.2 2072.96   119.2 2071.36     139 2067.35
   178.8 2058.04   248.3 2035.56   268.2 2030.16   278.1 2028.28   337.7 2019.73
   377.4 2015.26   417.1 2009.78   466.8 2000.13   496.6 1993.82   516.4 1990.72
   536.3  1988.8   556.2 1987.65     623 1985.58   635.6 1985.46     638 1985.91
   645.6 1987.34   655.5 1992.75   665.4 1999.45   675.4 2004.04   695.2 2010.72
   734.9 2027.74   754.8 2035.73   824.3 2062.37   913.7 2098.21   953.4 2112.92
#Mann= 3 , 0 , 0
       0      .1       0     623    .045       0     638      .1       0
Bank Sta=623,638
XS Rating Curve= 0 ,0
Exp/Cntr=0.3,0.1

Type RM Length L Ch R = 1 ,18677.9 ,305.1,300,292.4
XS GIS Cut Line= 3
     1972606.529      382774.953     1972073.413      382785.191
     1971457.621      382720.843
#Sta/Elev= 30
       0 2106.15    59.2 2088.07   108.6 2079.42     158 2068.53   266.6 2032.36
   276.5 2029.91   286.4 2028.84   335.7 2028.28   355.5 2026.16   424.6 2010.43
   444.4 2003.84     474 1991.55   513.5 1980.94   525.7 1979.11   533.2 1978.82
   540.7 1979.57   583.2 1988.65   623.1 1994.82     713 1996.23   772.9 2001.34
   812.8 2009.32   842.8 2018.32   862.8  2025.7   952.6 2065.45   982.6 2077.21
  1012.6 2087.19  1062.5 2100.05  1102.4 2112.18  1142.4 2129.11  1152.4 2132.16
#Mann= 3 , 0 , 0
       0     .06       0   525.7    .045       0   540.7     .06       0
Bank Sta=525.7,540.7
XS Rating Curve= 0 ,0
Exp/Cntr=0.3,0.1

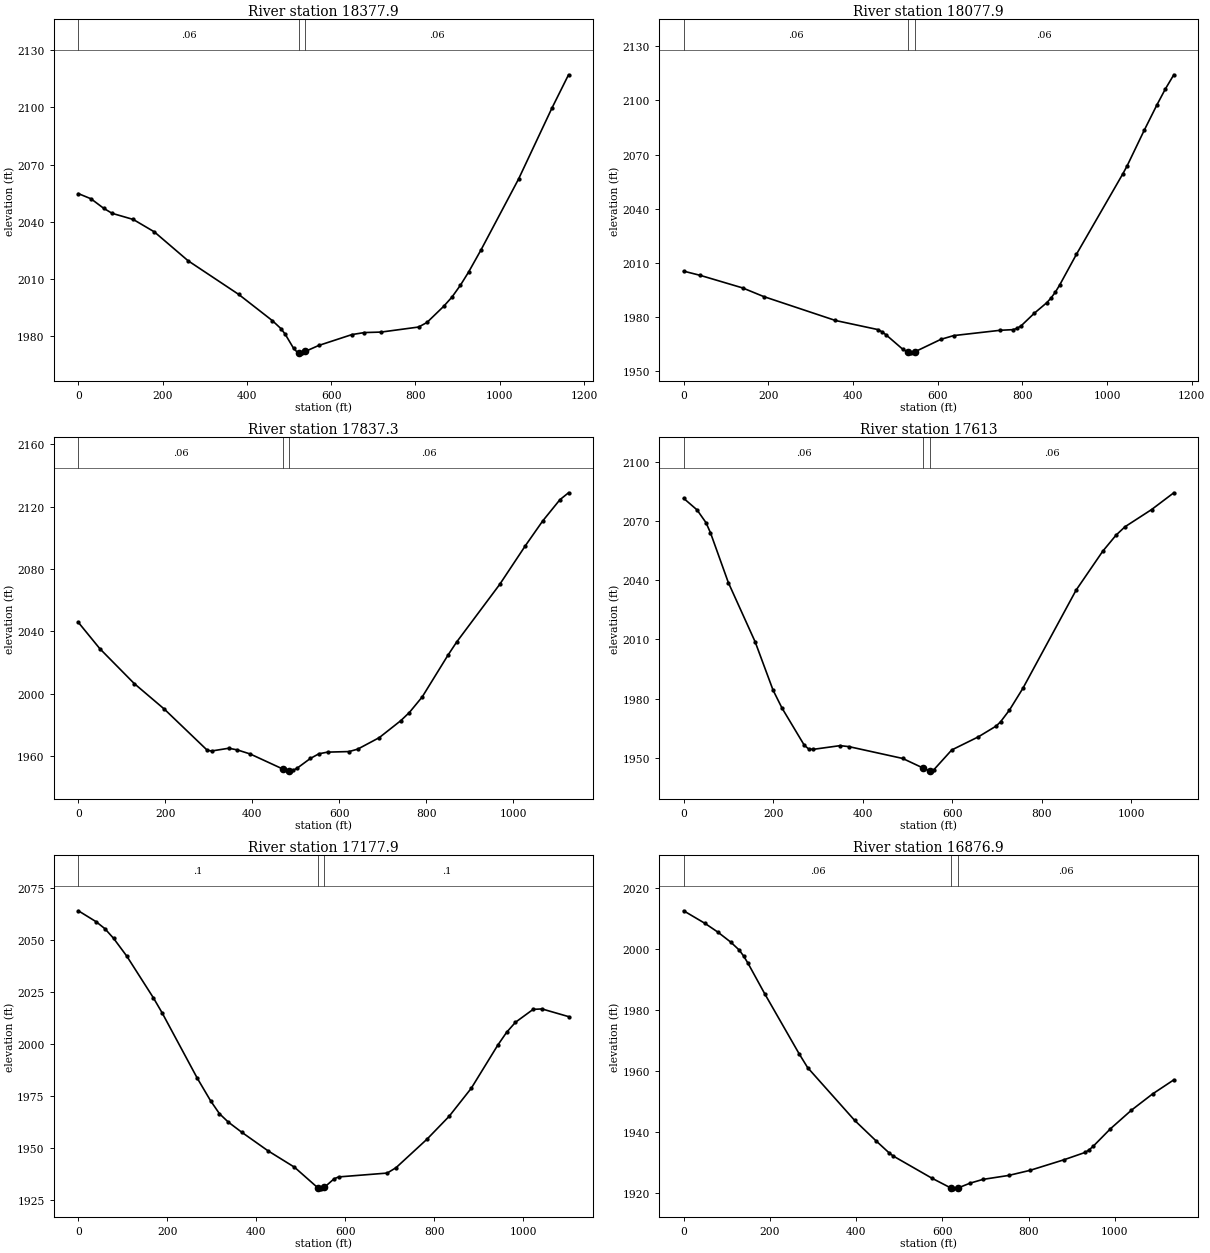
Type RM Length L Ch R = 1 ,18377.9 ,301.5,299.9,291.2
XS GIS Cut Line= 3
     1972584.928      382363.195     1972070.039      382491.918
     1971454.575      382637.719
#Sta/Elev= 30
       0 2054.72      30 2051.99    60.1    2047    80.1 2044.36   130.2 2041.14
   180.2 2034.63   260.4 2019.44   380.5 2001.76   460.6 1987.94   480.7 1983.79
   490.7 1980.89   510.7 1973.45   520.7  1971.1   523.2 1971.09   530.7 1971.06
   538.2 1971.77   570.3 1974.93   649.3 1980.66     679 1981.72   718.5 1981.97
   807.4 1984.62   827.2 1987.01   866.8 1995.47   886.5 2000.33   906.3 2006.47
     926 2013.49   955.7 2025.22  1044.6 2062.36  1123.7  2099.6  1163.2 2117.15
#Mann= 3 , 0 , 0
       0     .06       0   523.2    .045       0   538.2     .06       0
Bank Sta=523.2,538.2
XS Rating Curve= 0 ,0
Exp/Cntr=0.3,0.1

Type RM Length L Ch R = 1 ,18077.9 ,256.2,240.4,230.7
XS GIS Cut Line= 3
     1972455.906      382064.036     1971943.819      382228.404
     1971421.182      382561.767
#Sta/Elev= 30
       0 2005.26    39.8 2002.88   139.4 1995.94   189.2 1991.14   358.6 1977.87
   458.1 1972.86   468.1 1971.65   478.1 1969.91   517.9 1961.84   530.3 1960.19
   537.8 1959.91   545.3 1960.39   607.8 1967.42   637.8 1969.48   747.8 1972.43
   777.8 1972.78   787.8 1973.52   797.8 1975.06   827.8  1981.8   857.8 1987.76
   867.8 1990.36   877.8 1993.57   887.8 1997.41   927.8 2014.64  1037.7 2059.43
  1047.7 2063.82  1087.7 2083.38  1117.7 2097.48  1137.7 2106.36  1157.7 2114.26
#Mann= 3 , 0 , 0
       0     .06       0   530.3    .045       0   545.3     .06       0
Bank Sta=530.3,545.3
XS Rating Curve= 0 ,0
Exp/Cntr=0.3,0.1

Type RM Length L Ch R = 1 ,17837.3 ,222.3,224.3,227.7
XS GIS Cut Line= 3
     1972029.301      381674.691     1971752.036        382153.8
     1971384.241      382594.696
#Sta/Elev= 30
       0 2045.67    49.4 2028.79   128.5 2006.43   197.7 1990.03   296.6 1963.59
   306.4 1963.13     346  1964.9   365.7 1963.84   395.4 1961.21   470.2 1951.59
   484.4  1950.4   485.2 1950.43   494.2 1950.73   504.1 1952.26   533.8 1958.36
   553.6 1961.36   573.4 1962.41   622.8 1962.77   642.6 1964.32   692.1 1971.68
   741.6 1982.56   761.4  1987.8   791.1 1997.85   850.5 2024.71   870.3 2033.06
   969.3 2070.03  1028.7    2095  1068.3 2110.78  1107.9 2124.42  1127.7 2128.85
#Mann= 3 , 0 , 0
       0     .06       0   470.2    .045       0   485.2     .06       0
Bank Sta=470.2,485.2
XS Rating Curve= 0 ,0
Exp/Cntr=0.3,0.1

Type RM Length L Ch R = 1 ,17613   ,432.8,435.1,434.4
XS GIS Cut Line= 3
     1971910.363      381575.818     1971577.687      382013.113
     1971228.216      382432.465
#Sta/Elev= 30
       0 2081.49      30 2075.62      50 2069.15    59.9 2064.09    99.9 2038.82
   159.8 2008.82   199.8 1984.37   219.8 1975.28   269.7 1956.42   279.7 1954.52
   289.7 1954.38   349.6 1956.25   369.6 1955.74   489.5 1949.76   535.8 1944.83
   549.4 1943.49   550.8 1943.58   559.4 1944.12   599.1 1954.06   658.6 1960.71
   698.3 1966.16   708.3 1968.34   728.1 1974.28   757.9 1985.21     877    2035
   936.5 2054.69   966.3 2062.85   986.2 2067.07  1045.7  2075.8  1095.3 2084.29
#Mann= 3 , 0 , 0
       0     .06       0   535.8    .045       0   550.8     .06       0
Bank Sta=535.8,550.8
XS Rating Curve= 0 ,0
Exp/Cntr=0.3,0.1

Type RM Length L Ch R = 1 ,17177.9 ,299.3,301,305
XS GIS Cut Line= 3
     1971634.749      381321.711     1971261.554      381719.142
     1970923.254      382161.277
#Sta/Elev= 30
       0 2064.11    39.6 2058.89    59.5 2055.52    79.3 2050.82     109 2042.24
   168.5 2022.28   188.3    2015   267.6 1983.44   297.4 1972.63   317.2 1966.46
     337 1962.44   366.8 1957.62   426.2 1948.63   485.7 1940.74   537.7 1930.92
   545.2 1930.31   552.7 1930.98     575 1935.16     585 1936.04   694.3  1937.9
   714.2  1940.5   783.8 1954.22   833.5 1965.21   883.2 1978.69   942.8 1999.44
   962.7 2005.62   982.6 2010.46  1022.4 2016.68  1042.2 2016.88  1101.9 2013.19
#Mann= 3 , 0 , 0
       0      .1       0   537.7    .045       0   552.7      .1       0
Bank Sta=537.7,552.7
XS Rating Curve= 0 ,0
Exp/Cntr=0.3,0.1

Type RM Length L Ch R = 1 ,16876.9 ,287.3,303.2,319.1
XS GIS Cut Line= 3
     1971467.296      381150.865     1970880.855      381685.382
     1970647.378      381937.355
#Sta/Elev= 30
       0 2012.41    49.6 2008.28    79.4 2005.43   109.1 2002.18   128.9 1999.57
   138.9 1997.66   148.8 1995.37   188.4 1985.19   267.8 1965.66   287.6 1961.11
   396.7 1943.84   446.3 1937.15   476.1 1933.28     486  1932.2   575.3 1924.98
   621.2 1921.63   624.9 1921.45   636.2 1921.72   664.5 1923.31   694.3 1924.54
   753.8 1925.83   803.3 1927.49   881.8 1930.94   930.9 1933.34   940.7 1934.22
   950.5 1935.44   989.8 1941.07  1038.8 1947.19  1087.9 1952.51    1137  1957.1
#Mann= 3 , 0 , 0
       0     .06       0   621.2    .045       0   636.2     .06       0
Bank Sta=621.2,636.2
XS Rating Curve= 0 ,0
Exp/Cntr=0.3,0.1

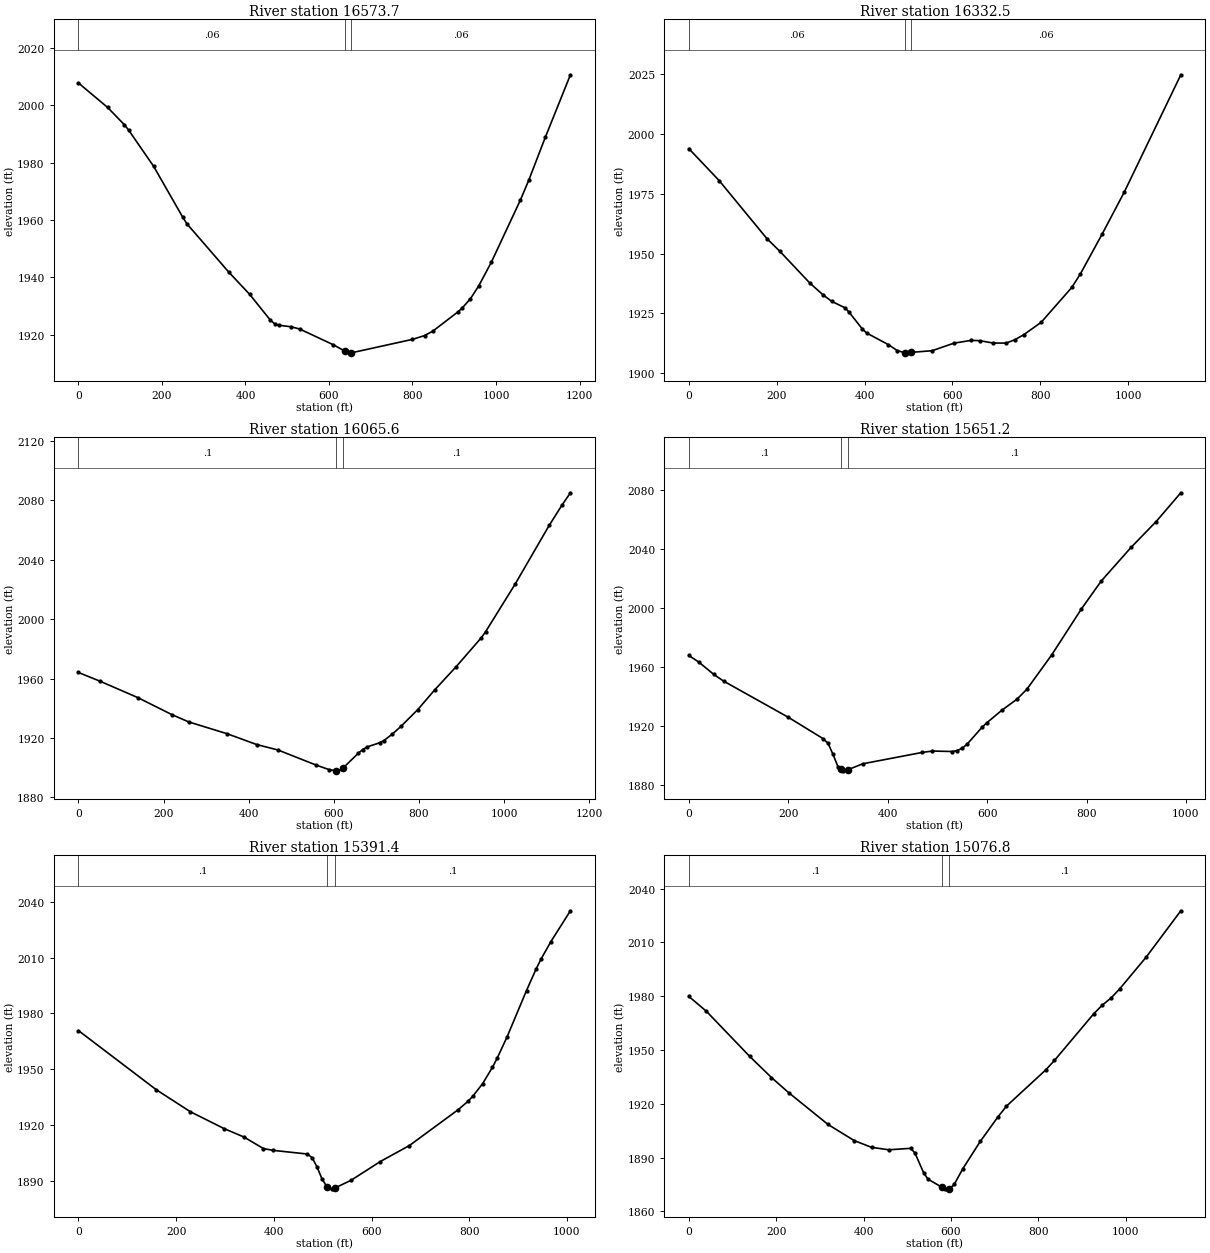
Type RM Length L Ch R = 1 ,16573.7 ,247.8,241.5,234.3
XS GIS Cut Line= 3
     1971455.292      381136.935     1971129.787      381312.747
     1970322.138       381343.35
#Sta/Elev= 30
       0 2007.84      70 1999.29     110 1993.26     120 1991.44     180 1978.76
     250 1960.93     260 1958.64     360 1941.82   409.9 1934.07   459.8 1925.02
   469.7 1923.81   479.7 1923.29   509.6 1922.73   529.6 1921.97   609.4 1916.53
   638.5 1914.22   649.3 1913.64   653.5 1913.64     799 1918.31   828.9 1919.66
   848.9 1921.24   908.8 1927.94   918.8 1929.24   938.7 1932.52   958.7 1937.03
   988.6 1945.21  1058.4 1966.98  1078.4 1973.88  1118.3 1988.97  1178.2 2010.71
#Mann= 3 , 0 , 0
       0     .06       0   638.5    .045       0   653.5     .06       0
Bank Sta=638.5,653.5
XS Rating Curve= 0 ,0
Exp/Cntr=0.3,0.1

Type RM Length L Ch R = 1 ,16332.5 ,262.5,265.9,272.2
XS GIS Cut Line= 3
     1971401.627      381062.288     1971076.335       381056.18
      1970302.05      381234.861
#Sta/Elev= 30
       0 1993.82      69 1980.48   177.5 1956.28     207 1950.98     276 1937.58
   305.6 1932.74   325.4 1930.03   355.2 1927.37   365.1 1925.45   394.9 1918.51
   404.8 1916.81   454.5 1911.94   474.3  1909.5   491.3  1908.6   494.2 1908.54
   506.3 1908.74   553.8 1909.43   603.5 1912.58   643.2 1913.76   663.1  1913.6
   692.9 1912.62   722.7 1912.62   742.5 1914.04   762.4 1916.11   802.1 1921.29
   871.7 1935.83   891.5 1941.55   941.2 1958.25   990.9 1975.54    1120 2024.67
#Mann= 3 , 0 , 0
       0     .06       0   491.3    .045       0   506.3     .06       0
Bank Sta=491.3,506.3
XS Rating Curve= 0 ,0
Exp/Cntr=0.3,0.1

Type RM Length L Ch R = 1 ,16065.6 ,421.6,414,406
XS GIS Cut Line= 3
     1971355.529      380809.229     1970879.328      380918.733
     1970213.474      380961.494
#Sta/Elev= 30
       0 1964.12    49.9 1958.35   139.6  1947.2   219.4 1935.78   259.3 1930.84
     349 1922.93   418.8 1915.64   468.7 1911.98   558.3 1901.83   588.2 1898.84
   605.7 1897.98   608.1 1897.94   618.1 1898.94   620.7 1899.56   657.9 1909.89
   667.9 1912.28   677.8 1913.99   707.7 1916.83   717.7 1918.31   737.6 1922.71
   757.5 1927.79   797.4 1939.19   837.2 1952.47     887 1967.88   946.7 1987.57
   956.7 1991.59  1026.4 2023.77  1106.1 2063.14  1135.9 2076.66  1155.9 2085.05
#Mann= 3 , 0 , 0
       0      .1       0   605.7    .045       0   620.7      .1       0
Bank Sta=605.7,620.7
XS Rating Curve= 0 ,0
Exp/Cntr=0.3,0.1

Type RM Length L Ch R = 1 ,15651.2 ,275.8,259.7,243.7
XS GIS Cut Line= 2
     1971088.553      380430.032     1970187.015      380838.425
#Sta/Elev= 30
       0 1967.88      20  1963.4      50 1955.08      70 1950.49   199.9 1926.03
   269.9 1911.56   279.9 1908.42   289.9 1900.97   299.9 1892.54   305.3 1891.01
   309.9 1889.71   320.3 1890.51   349.9 1894.49   469.9 1902.21   489.9 1903.12
   529.8 1902.81   539.8 1903.46   549.8 1905.04   559.8 1907.79   589.8 1919.22
   599.8 1922.38   629.8  1930.8   659.8 1938.18   679.8 1944.92   729.8 1968.18
   789.8 1999.46   829.8 2018.38   889.8 2041.17   939.7 2058.47   989.7 2078.11
#Mann= 3 , 0 , 0
       0      .1       0   305.3    .045       0   320.3      .1       0
Bank Sta=305.3,320.3
XS Rating Curve= 0 ,0
Exp/Cntr=0.3,0.1

Type RM Length L Ch R = 1 ,15391.4 ,303.4,314.6,330.7
XS GIS Cut Line= 3
     1970822.822      379938.277     1970520.439       380588.86
     1970265.398      380726.307
#Sta/Elev= 30
       0 1970.74   159.4 1938.92   229.2 1927.08   298.9 1917.93   338.8 1913.49
   378.6 1907.28   398.6 1906.32   468.3 1904.35   478.3 1902.43   488.2  1897.5
   498.2 1891.18   508.2 1886.88   509.7 1886.69   518.1 1885.62   524.7 1886.04
     558 1890.21   617.8 1900.29   677.6 1908.93   777.4  1928.2   797.3 1932.68
   807.3 1935.45   827.3 1942.18   847.3  1950.9   857.3 1955.96   877.3 1967.28
   917.2 1992.28   937.2 2004.08   947.2 2009.33   967.2 2018.64  1007.1 2035.19
#Mann= 3 , 0 , 0
       0      .1       0   509.7    .045       0   524.7      .1       0
Bank Sta=509.7,524.7
XS Rating Curve= 0 ,0
Exp/Cntr=0.3,0.1

Type RM Length L Ch R = 1 ,15076.8 ,291.7,299.8,304.1
XS GIS Cut Line= 3
     1970832.591      379878.145     1970360.301      380227.279
     1969868.024      380446.069
#Sta/Elev= 30
       0 1979.89    39.8  1971.7   139.4 1946.42   189.1 1934.66     229 1926.12
   318.6 1908.48   378.3 1899.52   418.1 1895.72   457.9 1894.36   507.7 1895.19
   517.6 1892.53   537.6  1881.4   547.5 1877.98   579.8 1873.39   587.3 1872.59
   594.8 1872.68   597.3 1872.71   607.3 1875.04   627.2 1883.86   667.1 1899.08
     707 1912.56     727 1918.72   816.8  1938.9   836.7 1944.17   926.5 1970.16
   946.5  1975.1   966.4 1979.03   986.4  1984.2  1046.2 2001.66    1126 2027.66
#Mann= 3 , 0 , 0
       0      .1       0   579.8    .045       0   594.8      .1       0
Bank Sta=579.8,594.8
XS Rating Curve= 0 ,0
Exp/Cntr=0.3,0.1

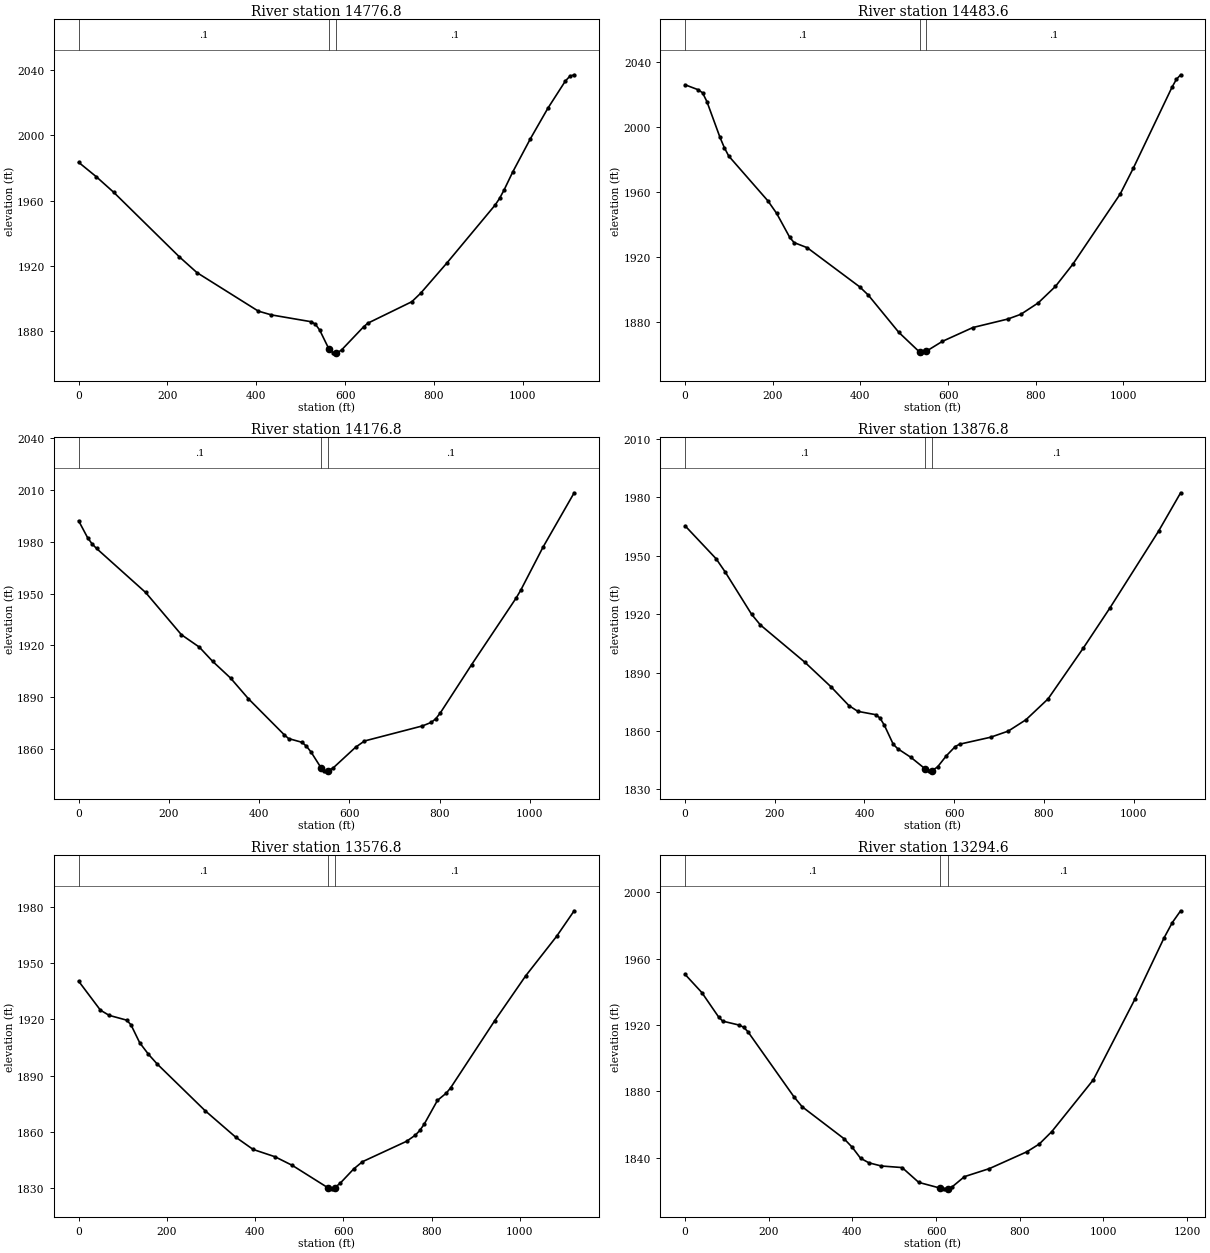
Type RM Length L Ch R = 1 ,14776.8 ,305.9,293.2,279.3
XS GIS Cut Line= 3
     1970796.895      379800.927     1970247.012      379959.427
     1969717.766       380082.83
#Sta/Elev= 30
       0 1983.42    39.5 1974.66    78.9 1965.08   226.9 1925.51   266.4 1915.88
   404.5 1892.32   434.1 1889.99   522.9 1885.85   532.8  1884.4   542.7 1880.72
   562.4 1869.75   564.8 1869.06   572.3 1866.91   579.8  1866.8   582.2 1866.77
     592 1868.54   641.4 1882.64   651.3 1884.95   750.1 1898.06   769.9 1903.21
   829.2  1921.8   937.9 1957.31   947.7 1961.32   957.6 1966.33   977.4 1977.52
  1016.9 1997.74  1056.4 2016.49    1096 2033.24  1105.8 2036.05  1115.7 2037.01
#Mann= 3 , 0 , 0
       0      .1       0   564.8    .045       0   579.8      .1       0
Bank Sta=564.8,579.8
XS Rating Curve= 0 ,0
Exp/Cntr=0.3,0.1

Type RM Length L Ch R = 1 ,14483.6 ,301.7,306.8,311.8
XS GIS Cut Line= 3
     1970531.609      379289.606     1970024.102      379863.445
     1969683.273      379992.601
#Sta/Elev= 30
       0 2026.18    29.8 2023.14    39.8 2021.25    49.7 2015.87    79.6 1993.78
    89.5 1987.44    99.5 1982.29     189 1954.62   208.9 1946.93   238.8 1932.12
   248.7 1928.93   278.6 1925.79     398 1901.73   417.8 1896.63   487.5 1873.64
   535.5 1861.33   537.2    1861   550.5 1862.02     587 1868.08   656.6  1876.6
   736.2 1881.82   766.1 1884.77   805.5 1891.76   844.9 1901.94   884.3 1915.52
   992.6 1958.87  1022.2 1974.61  1110.8 2024.68  1120.7  2029.5  1130.5 2032.35
#Mann= 3 , 0 , 0
       0      .1       0   535.5    .045       0   550.5      .1       0
Bank Sta=535.5,550.5
XS Rating Curve= 0 ,0
Exp/Cntr=0.3,0.1

Type RM Length L Ch R = 1 ,14176.8 ,297.2,299.9,299.8
XS GIS Cut Line= 3
     1970430.661      379140.258     1969988.086      379457.403
     1969538.889      379780.823
#Sta/Elev= 30
       0 1992.01    19.8 1982.29    29.7 1978.72    39.6 1976.06   148.5 1950.61
   227.7 1926.23   267.3 1919.09     297 1910.82   336.6  1901.2   376.2 1889.25
   455.4 1868.49   465.3 1866.24     495 1864.08   504.9 1861.78   514.8 1858.55
     537 1849.42   544.5 1847.63     552 1847.61   564.2 1849.33   613.7 1861.25
   633.4 1864.85   761.9 1873.56   781.7 1875.63   791.6 1877.78   801.5  1881.1
   870.6 1908.88   969.5 1947.45   979.4 1951.83  1028.8 1976.72    1098  2008.2
#Mann= 3 , 0 , 0
       0      .1       0     537    .045       0     552      .1       0
Bank Sta=537,552
XS Rating Curve= 0 ,0
Exp/Cntr=0.3,0.1

Type RM Length L Ch R = 1 ,13876.8 ,306.2,300,291.9
XS GIS Cut Line= 3
     1970286.875      378961.859     1969810.902      379223.645
     1969358.075      379556.138
#Sta/Elev= 30
       0  1965.4    69.1 1948.51    88.9 1941.88   148.2 1919.99   167.9 1914.48
   266.7 1895.41   325.9 1882.59   365.4 1873.04   385.2 1870.11   424.7 1868.41
   434.6 1866.68   444.4 1862.93   464.2 1853.18   474.1 1850.92   503.7 1846.45
   535.7 1840.49   543.2 1839.55   550.7 1839.67   562.9 1841.55   582.6 1847.29
   602.4 1852.03   612.2 1853.24   681.2 1856.81   720.6 1859.96     760 1865.78
   809.3 1876.49   888.2  1902.7   947.3 1923.22  1055.7 1962.64    1105 1982.38
#Mann= 3 , 0 , 0
       0      .1       0   535.7    .045       0   550.7      .1       0
Bank Sta=535.7,550.7
XS Rating Curve= 0 ,0
Exp/Cntr=0.3,0.1

Type RM Length L Ch R = 1 ,13576.8 ,267.8,282.2,301.5
XS GIS Cut Line= 3
     1969993.076      378618.591     1969596.899      379033.116
     1969298.063       379494.33
#Sta/Elev= 30
       0  1940.4    49.4 1924.94    69.2 1922.18   108.8 1919.63   118.6 1917.16
   138.4 1907.58   158.2 1901.45     178 1896.27   286.7 1871.36   355.9 1857.28
   395.4 1850.73   444.9 1846.84   484.4 1842.21   565.9 1830.16   573.4 1829.73
   580.9 1830.41   593.4 1832.89   623.4 1840.34   643.3  1844.2   743.3 1855.08
   763.2 1858.37   773.2 1860.86   783.2 1864.22   813.2 1876.88   833.2 1880.74
   843.2 1883.61   943.1  1919.4    1013  1943.2    1083 1964.23    1123 1977.91
#Mann= 3 , 0 , 0
       0      .1       0   565.9    .045       0   580.9      .1       0
Bank Sta=565.9,580.9
XS Rating Curve= 0 ,0
Exp/Cntr=0.3,0.1

Type RM Length L Ch R = 1 ,13294.6 ,162.1,159.3,156.5
XS GIS Cut Line= 3
     1969940.631      378557.509     1969665.213      378818.847
     1968867.353      378925.977
#Sta/Elev= 30
       0  1950.5      40 1939.56    79.9 1924.92    89.9 1922.33   129.9 1919.91
   139.9 1918.64   149.9 1916.05   259.8 1876.88   279.8 1870.73   379.7 1851.52
   399.6 1846.29   419.4 1839.71   439.3 1836.93   469.1 1835.01   518.8 1834.07
   558.6 1825.13   608.3 1821.77   618.2 1821.24   628.1 1821.26   638.1 1822.36
   667.9  1828.6   727.5 1833.44     817 1843.57   846.8 1848.27   876.6 1855.73
     976 1886.98  1075.4 1935.58  1144.9 1972.44  1164.8 1981.75  1184.7 1988.85
#Mann= 3 , 0 , 0
       0      .1       0   608.3    .045       0   628.1      .1       0
Bank Sta=608.3,628.1
XS Rating Curve= 0 ,0
Exp/Cntr=0.3,0.1