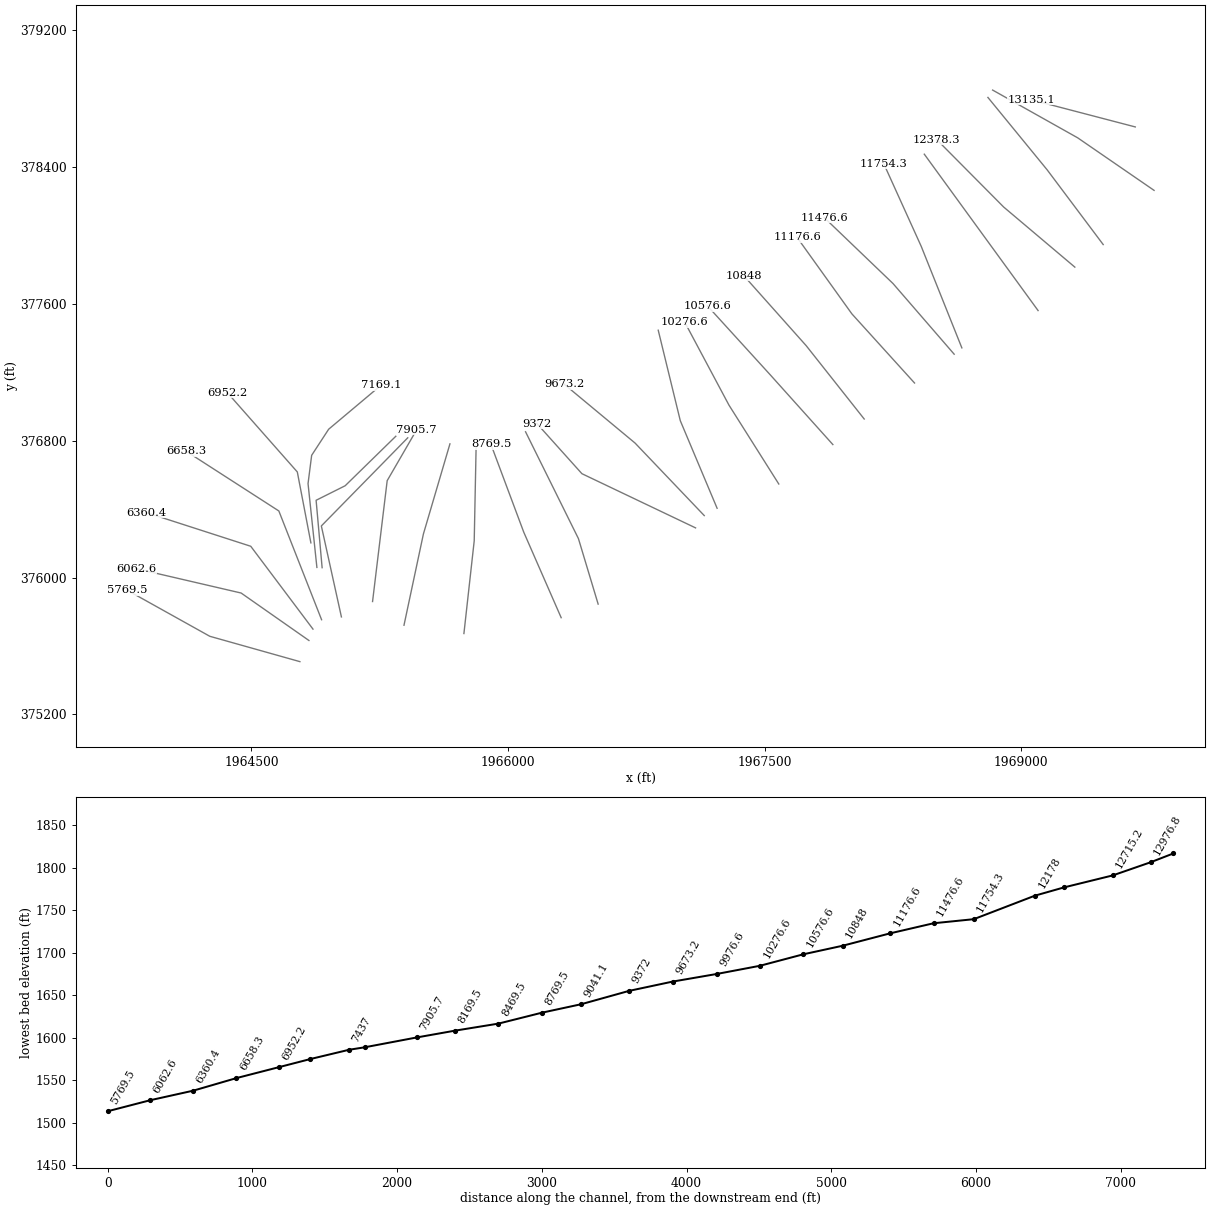
HEC-RAS study KeeneyCrk.prj: KeeneyCrk

--- KeeneyCrk.g01 (geometry) --- (continued)

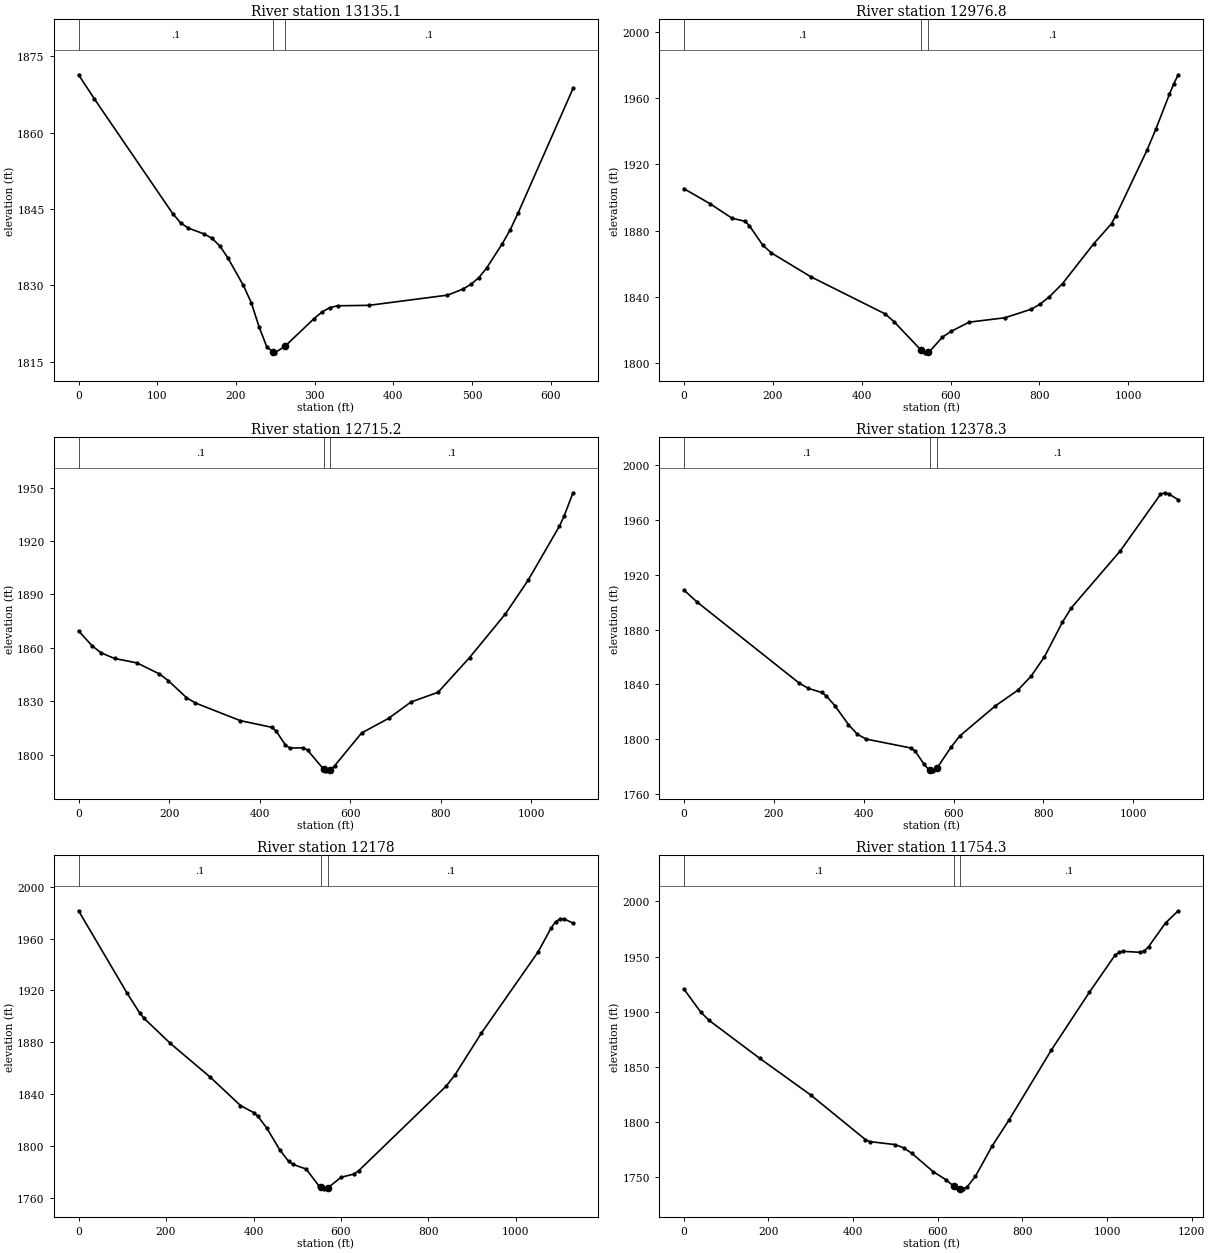
Type RM Length L Ch R = 1 ,13135.1 ,166.2,158.3,152.5
XS GIS Cut Line= 2
     1969666.231      378634.397     1969058.409      378793.225
#Sta/Elev= 30
       0 1871.33    19.9 1866.64   119.7 1844.08   129.6 1842.28   139.6 1841.24
   159.6  1840.1   169.5 1839.26   179.5 1837.74   189.5 1835.45   209.4    1830
   219.4 1826.63   229.4 1821.85   239.3 1817.89   247.2 1817.01   249.3 1816.78
   262.2 1818.06   299.2  1823.5   309.1 1824.77   319.1 1825.64   329.1 1826.01
     369  1826.1   468.7  1828.1   488.6  1829.3   498.6 1830.24   508.6 1831.54
   518.5 1833.43   538.5 1838.22   548.4 1840.92   558.4 1844.19   628.2 1868.64
#Mann= 3 , 0 , 0
       0      .1       0   247.2    .045       0   262.2      .1       0
Bank Sta=247.2,262.2
XS Rating Curve= 0 ,0
Exp/Cntr=0.3,0.1

Type RM Length L Ch R = 1 ,12976.8 ,268.8,261.6,253.2
XS GIS Cut Line= 3
     1969776.054      378263.606     1969329.763       378570.62
     1968832.396      378849.889
#Sta/Elev= 30
       0 1905.42    59.1 1896.28   108.3 1887.58   137.9  1885.7   147.7 1882.97
   177.3 1871.38     197 1866.61   285.6 1852.25     453  1829.8   472.8 1825.14
   534.2 1807.79   541.7 1806.33   549.2 1806.69   551.7 1806.81   581.7 1815.83
   601.7 1819.35   641.8 1824.85   721.8 1827.47   781.9 1832.69   801.9 1835.84
   821.9 1840.08   851.9 1848.14     922 1872.14     962 1884.28     972 1889.19
    1042 1928.71  1062.1 1941.57  1092.1 1962.26  1102.1 1968.69  1112.1 1974.11
#Mann= 3 , 0 , 0
       0      .1       0   534.2    .045       0   549.2      .1       0
Bank Sta=534.2,549.2
XS Rating Curve= 0 ,0
Exp/Cntr=0.3,0.1

Type RM Length L Ch R = 1 ,12715.2 ,332.8,336.7,338.8
XS GIS Cut Line= 3
     1969478.697      377946.825     1969151.183      378383.513
     1968804.938      378806.724
#Sta/Elev= 30
       0 1869.51    29.8 1861.19    49.6 1857.22    79.4 1854.04     129 1851.54
   178.6 1845.34   198.5 1841.52   238.2 1832.08     258 1829.02   357.3  1819.1
   426.8 1815.34   436.7  1813.2   456.5 1805.65   466.5 1803.65   496.2 1803.84
   506.2 1802.49   541.3 1791.85   545.9 1790.87   556.3 1791.38   565.7 1793.66
   625.4 1812.13     685 1820.33   734.8 1829.58   794.4 1835.01     864 1854.49
   943.5 1879.14   993.2 1897.87  1062.8 1928.45  1072.8 1933.92  1092.7 1947.16
#Mann= 3 , 0 , 0
       0      .1       0   541.3    .045       0   556.3      .1       0
Bank Sta=541.3,556.3
XS Rating Curve= 0 ,0
Exp/Cntr=0.3,0.1

Type RM Length L Ch R = 1 ,12378.3 ,205.6,200.8,196.9
XS GIS Cut Line= 3
      1969312.92      377814.981     1968896.992      378166.165
     1968505.721      378560.345
#Sta/Elev= 30
       0 1908.91    29.7    1900   257.3 1840.68   277.1    1837   306.8 1833.99
   316.7 1831.57   336.5 1824.18   366.2 1810.58     386 1803.48   405.8 1799.94
   504.8 1793.49   514.7  1791.1   534.5 1781.56   544.4 1777.76   548.6 1777.34
   554.3 1776.77   563.6    1779     594 1793.87   613.8 1802.23   693.1 1824.24
   742.7 1835.59   772.5 1845.92   802.2 1860.09   841.9 1885.23   861.7 1895.69
   970.8  1937.4  1060.1 1978.62    1070 1979.86  1079.9 1978.82  1099.8 1974.77
#Mann= 3 , 0 , 0
       0      .1       0   548.6    .045       0   563.6      .1       0
Bank Sta=548.6,563.6
XS Rating Curve= 0 ,0
Exp/Cntr=0.3,0.1

Type RM Length L Ch R = 1 ,12178   ,427.4,422.7,418.8
XS GIS Cut Line= 2
     1969098.072      377560.988     1968432.948      378475.114
#Sta/Elev= 30
       0  1981.4     110  1918.4   140.1 1902.43   150.1 1898.38   210.1  1879.1
   300.1 1853.43   370.2 1831.29   400.2 1825.86   410.2 1822.92   430.2 1813.95
   460.2 1797.01   480.2 1788.24   490.2 1785.88   520.2 1782.36   550.2 1769.06
   554.6 1768.18   560.2 1767.06   569.6 1767.76   600.3 1775.94   630.3 1778.54
   640.3 1780.96   840.4 1846.22   860.4 1854.76   920.4 1886.81  1050.5 1949.58
  1080.5 1968.14  1090.5 1972.84  1100.5 1975.06  1110.5  1975.1  1130.5 1971.87
#Mann= 3 , 0 , 0
       0      .1       0   554.6    .045       0   569.6      .1       0
Bank Sta=554.6,569.6
XS Rating Curve= 0 ,0
Exp/Cntr=0.3,0.1

Type RM Length L Ch R = 1 ,11754.3 ,270.3,277.6,286.3
XS GIS Cut Line= 3
     1968652.462      377342.899      1968415.14      377936.037
     1968196.686      378418.176
#Sta/Elev= 30
       0  1920.6    39.9 1899.68    59.9 1892.08   179.7 1857.61   299.5 1824.57
   429.2 1784.03   439.2 1782.23   499.1  1779.5   519.1 1776.61     539 1771.51
   588.9 1755.06   618.9 1747.78   638.3 1741.56   648.8 1739.42   653.3 1739.41
   658.8 1739.39   668.8 1740.92   688.8 1750.61   728.7 1778.34   768.7    1802
   868.6 1865.37   958.4 1917.72  1018.4 1951.02  1028.4 1953.96  1038.3  1954.7
  1078.3 1953.84  1088.3 1955.13  1098.3 1959.07  1138.2 1980.49  1168.2  1991.5
#Mann= 3 , 0 , 0
       0      .1       0   638.3    .045       0   653.3      .1       0
Bank Sta=638.3,653.3
XS Rating Curve= 0 ,0
Exp/Cntr=0.3,0.1

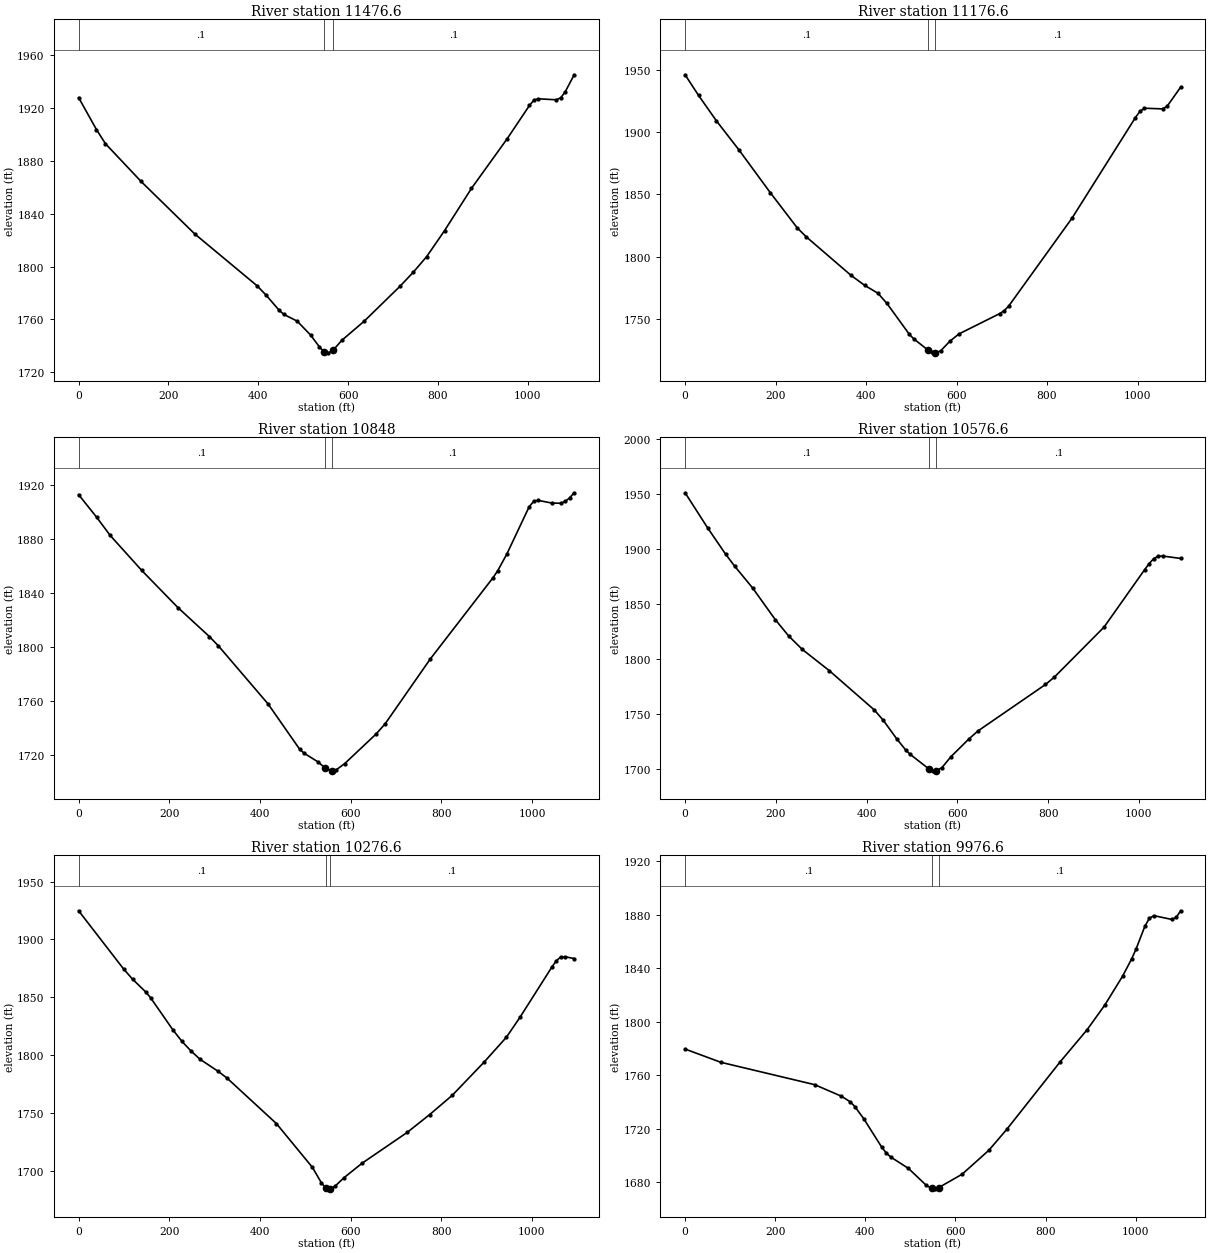
Type RM Length L Ch R = 1 ,11476.6 ,299.5,300,295.8
XS GIS Cut Line= 3
     1968607.539      377306.032     1968250.111       377718.98
     1967848.066      378104.551
#Sta/Elev= 30
       0 1927.92    39.7 1903.72    59.6 1893.07     139 1864.43   258.2 1824.76
   397.2 1785.41   417.1 1778.41   446.8 1766.68   456.8 1763.74   486.6  1758.6
   516.4 1748.08   536.2 1739.03   546.2 1735.47   556.1  1734.6     566 1736.38
   585.9 1744.07   635.7 1758.56   715.3 1784.96   745.1 1795.69   774.9 1807.53
   814.7  1827.2   874.4  1859.1     954 1896.75  1003.7 1922.02  1013.7 1926.08
  1023.6 1927.04  1063.4 1926.28  1073.4 1927.85  1083.3 1932.34  1103.2 1945.23
#Mann= 3 , 0 , 0
       0      .1       0   546.2    .045       0     566      .1       0
Bank Sta=546.2,566
XS Rating Curve= 0 ,0
Exp/Cntr=0.3,0.1

Type RM Length L Ch R = 1 ,11176.6 ,329.8,328.6,331
XS GIS Cut Line= 3
     1968375.881      377137.615     1968009.709      377541.666
     1967689.314      377988.746
#Sta/Elev= 30
       0 1945.77    29.7 1929.25    69.4 1908.74     119 1885.53   188.4 1851.18
   247.9 1822.96   267.7 1815.82   366.8 1784.87   396.6 1776.94   426.3 1770.52
   446.2 1762.33   495.7 1737.56   505.6 1733.89   537.8 1724.69   545.3 1723.02
   552.8 1722.81   555.3 1722.74   565.3 1724.52   585.3 1732.08   605.3  1737.9
   695.3 1754.19   705.3 1756.55   715.3 1760.28   855.3 1830.82   995.3 1911.42
  1005.3 1916.43  1015.3 1918.95  1055.3 1918.41  1065.3 1920.46  1095.3 1935.83
#Mann= 3 , 0 , 0
       0      .1       0   537.8    .045       0   552.8      .1       0
Bank Sta=537.8,552.8
XS Rating Curve= 0 ,0
Exp/Cntr=0.3,0.1

Type RM Length L Ch R = 1 ,10848   ,270.3,271.4,271.6
XS GIS Cut Line= 3
     1968081.654      376927.161     1967742.175      377356.252
     1967379.017      377763.698
#Sta/Elev= 30
       0 1912.46    39.8 1895.75    69.6 1882.31   139.3 1856.38   218.9 1828.96
   288.5 1807.46   308.4 1800.55   417.8 1757.64   487.4 1724.14   497.4 1721.14
   527.2 1714.91   544.2 1710.15   557.1 1708.13   559.2 1708.23     567 1708.59
   586.8 1713.48   656.3 1735.46   676.2 1743.02   775.4 1790.83   914.3 1851.19
   924.2 1856.17   944.1 1868.35   993.7 1903.59  1003.6  1907.5  1013.6 1908.26
  1043.3 1906.29  1063.2 1906.13  1073.1 1907.46    1083 1910.19  1092.9 1913.88
#Mann= 3 , 0 , 0
       0      .1       0   544.2    .045       0   559.2      .1       0
Bank Sta=544.2,559.2
XS Rating Curve= 0 ,0
Exp/Cntr=0.3,0.1

Type RM Length L Ch R = 1 ,10576.6 ,303.8,300,294.4
XS GIS Cut Line= 3
     1967898.421      376777.804     1967533.653      377184.104
     1967166.017      377587.782
#Sta/Elev= 30
       0 1951.44    49.6  1919.5    89.4 1895.43   109.2 1884.58   148.9 1864.65
   198.6 1835.93   228.3 1820.94   258.1 1808.77   317.7 1789.39     417 1753.55
   436.8 1744.08   466.6 1727.12   486.4 1716.93   496.4 1712.98   538.5 1699.41
     546 1698.08   553.5  1698.2   565.9 1700.96   585.7 1710.91   625.4 1727.14
   645.3  1734.4   794.2 1776.77     814 1783.59   923.2 1829.04  1012.6 1881.35
  1022.5 1886.86  1032.4 1891.33  1042.4 1893.67  1052.3 1893.79    1092 1891.62
#Mann= 3 , 0 , 0
       0      .1       0   538.5    .045       0   553.5      .1       0
Bank Sta=538.5,553.5
XS Rating Curve= 0 ,0
Exp/Cntr=0.3,0.1

Type RM Length L Ch R = 1 ,10276.6 ,303.7,300,294.4
XS GIS Cut Line= 3
     1967582.339      376547.295     1967290.966      377008.638
     1967033.211      377492.205
#Sta/Elev= 30
       0 1924.78    99.2 1874.52     119  1865.7   148.8 1854.37   158.7 1849.69
   208.3 1821.74   228.2 1811.88     248 1803.65   267.9  1796.5   307.6 1786.15
   327.4 1780.27   436.5 1740.93   515.9 1703.12   535.7  1689.8   545.6 1685.22
   555.6 1684.56   565.6 1686.74   585.5 1694.12   625.4 1706.65     725 1733.28
   774.8 1748.75   824.6 1765.37   894.4 1793.86   944.2  1815.6   974.1 1832.82
  1043.8 1875.79  1053.8 1881.42  1063.7 1884.79  1073.7 1885.07  1093.6  1883.5
#Mann= 3 , 0 , 0
       0      .1       0   545.6    .045       0   555.6      .1       0
Bank Sta=545.6,555.6
XS Rating Curve= 0 ,0
Exp/Cntr=0.3,0.1

Type RM Length L Ch R = 1 ,9976.6  ,294.9,303.5,317.8
XS GIS Cut Line= 3
     1967221.857      376405.402     1967006.705       376917.24
     1966877.712       377446.11
#Sta/Elev= 30
       0 1779.46    79.3 1769.56   287.5 1752.82     347 1744.17   366.8 1739.91
   376.8 1736.36   396.6 1727.26   436.2 1706.11   446.2 1701.74   456.1 1698.74
   495.7 1690.13   535.4 1677.43   547.7 1675.16   555.2 1674.88   562.7 1675.79
   614.6 1685.79     674 1703.72   713.6 1719.31   832.4 1769.94   891.7 1793.77
   931.3 1812.36   970.9 1834.05   990.7 1846.82  1000.6 1854.22  1020.4 1871.48
  1030.3 1877.31  1040.2 1879.28  1079.8 1876.45  1089.7 1877.91  1099.6 1882.92
#Mann= 3 , 0 , 0
       0      .1       0   547.7    .045       0   562.7      .1       0
Bank Sta=547.7,562.7
XS Rating Curve= 0 ,0
Exp/Cntr=0.3,0.1

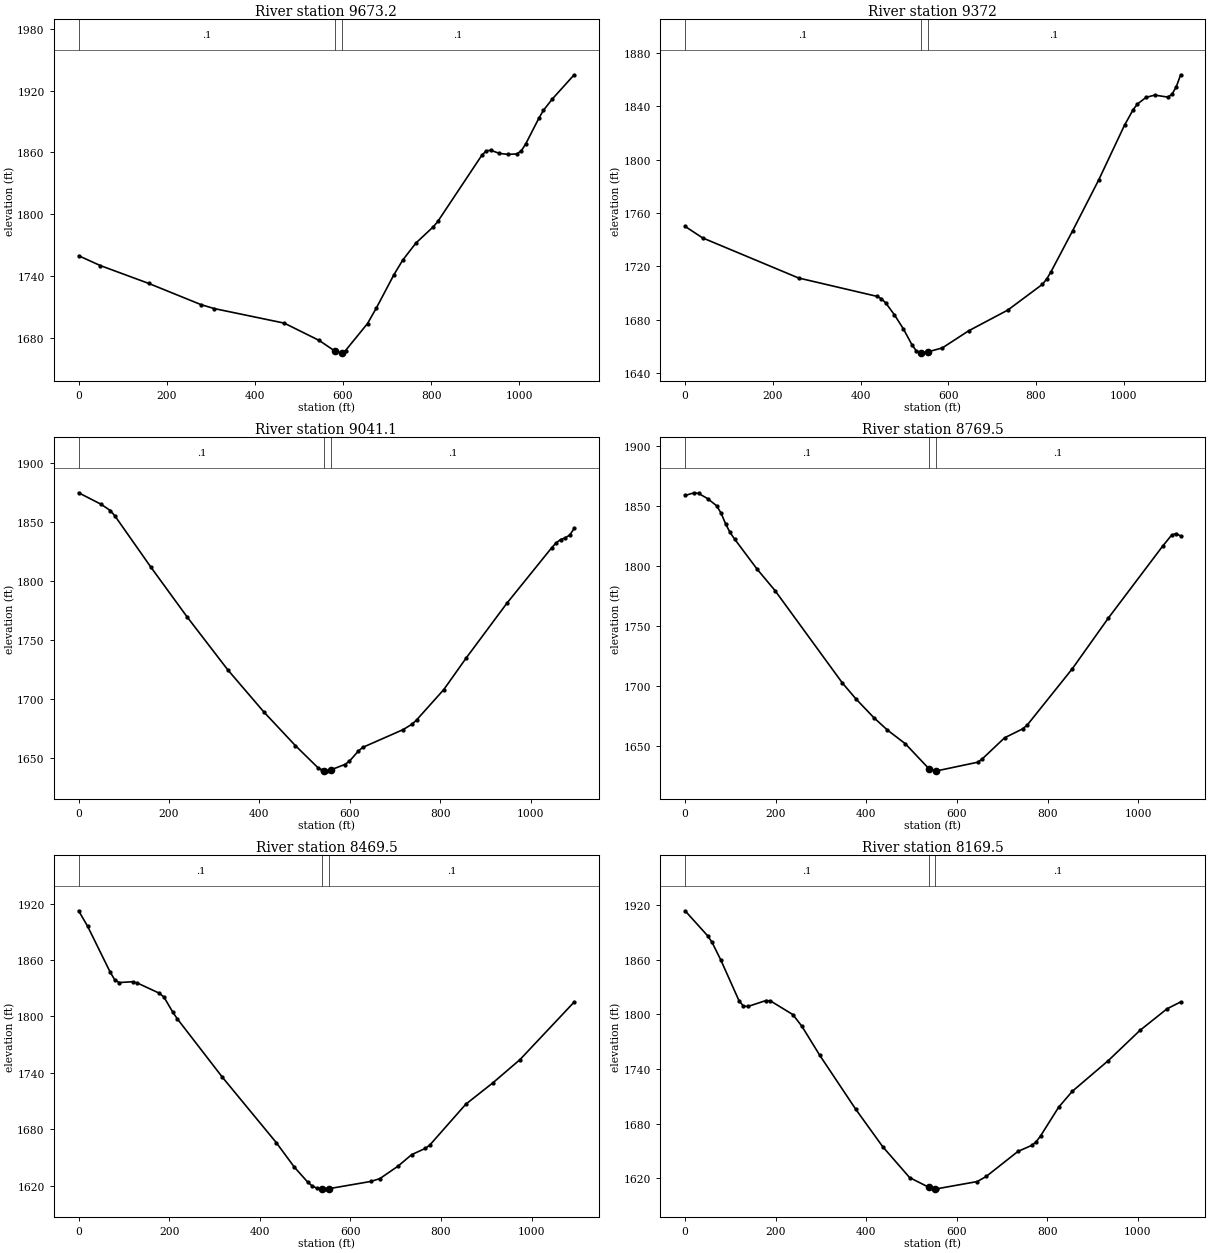
Type RM Length L Ch R = 1 ,9673.2  ,293.3,301,306.6
XS GIS Cut Line= 3
      1967146.77      376362.575     1966742.326      376786.455
      1966327.76      377130.862
#Sta/Elev= 30
       0    1760    49.6 1750.42   158.9 1733.22     278 1712.61   307.8 1708.83
   466.7 1694.74   546.2 1677.92   581.7 1667.65   595.9 1665.96   596.7 1666.14
   605.8 1668.18   655.7 1694.32   675.7 1709.29   715.6 1741.57   735.6 1755.73
   765.5 1772.26   805.4 1788.19   815.4 1793.28   915.2 1857.33   925.2 1861.52
   935.2 1862.17   955.2 1859.08   975.1 1858.14   995.1 1858.62  1005.1  1861.8
    1015 1868.42    1045 1893.48    1055 1900.75  1074.9 1911.66  1124.8 1935.25
#Mann= 3 , 0 , 0
       0      .1       0   581.7    .045       0   596.7      .1       0
Bank Sta=581.7,596.7
XS Rating Curve= 0 ,0
Exp/Cntr=0.3,0.1

Type RM Length L Ch R = 1 ,9372    ,346,330.8,315.6
XS GIS Cut Line= 3
     1967095.998      376290.688     1966431.644      376607.477
     1966168.409      376900.653
#Sta/Elev= 30
       0 1749.86    39.8 1741.25   258.6 1711.18   437.6 1697.39   447.6 1695.63
   457.5 1692.48   477.4  1683.5   497.3 1673.25   517.2 1661.15   527.2 1656.49
   537.1 1655.03   538.3 1655.07   553.3 1655.71   586.8 1658.76   646.5 1671.53
     736 1687.12   814.8 1706.42   824.7 1710.47   834.5  1715.9   883.8 1746.63
   942.9 1784.53    1002 1825.74  1021.7 1837.39  1031.5 1841.65  1051.2 1846.63
  1070.9 1848.33  1100.5 1846.85  1110.3 1848.93  1120.2  1854.7    1130 1863.57
#Mann= 3 , 0 , 0
       0      .1       0   538.3    .045       0   553.3      .1       0
Bank Sta=538.3,553.3
XS Rating Curve= 0 ,0
Exp/Cntr=0.3,0.1

Type RM Length L Ch R = 1 ,9041.1  ,272.6,271.5,269.2
XS GIS Cut Line= 3
     1966526.497       375845.19     1966411.281      376228.056
     1966102.202      376852.421
#Sta/Elev= 30
       0 1874.62      50 1864.83      70 1859.61      80 1855.21   159.9 1811.66
   239.9 1769.65   329.9 1724.86   409.8 1689.18   479.4 1660.78   529.2 1642.13
   539.2 1639.78   543.3  1639.6   549.1 1639.34   558.3  1640.2   588.9  1644.7
   598.9 1647.37   618.8 1656.02   628.7  1659.2   718.3 1674.27   738.2 1678.94
   748.2 1682.56   807.9 1708.06   857.6 1734.84   947.2 1780.95  1046.7 1828.08
  1056.7 1832.29  1066.6 1835.08  1076.6 1836.49  1086.6 1838.81  1096.5 1844.45
#Mann= 3 , 0 , 0
       0      .1       0   543.3    .045       0   558.3      .1       0
Bank Sta=543.3,558.3
XS Rating Curve= 0 ,0
Exp/Cntr=0.3,0.1

Type RM Length L Ch R = 1 ,8769.5  ,311.8,300.1,291.4
XS GIS Cut Line= 3
     1966310.412      375765.797     1966091.662      376265.602
     1965899.913      376778.767
#Sta/Elev= 30
       0 1859.05    19.8 1861.31    29.8 1860.77    49.6 1856.47    69.4 1850.53
    79.4 1844.36    89.3 1835.42    99.2 1828.19   109.1 1822.77   158.7  1797.7
   198.4 1779.75   347.2 1702.58     377 1689.35   416.6 1673.69   446.4  1663.4
   486.1 1651.92   538.1  1631.1   553.1 1629.41   555.5 1629.37   645.2 1636.52
   655.1  1639.1   704.9 1656.92   744.8 1664.37   754.8 1667.52   854.4 1714.55
     934 1756.86  1053.6 1816.74  1073.5 1825.99  1083.4  1827.3  1093.4 1825.28
#Mann= 3 , 0 , 0
       0      .1       0   538.1    .045       0   553.1      .1       0
Bank Sta=538.1,553.1
XS Rating Curve= 0 ,0
Exp/Cntr=0.3,0.1

Type RM Length L Ch R = 1 ,8469.5  ,302.2,300,294.1
XS GIS Cut Line= 3
     1965741.879      375673.135     1965802.123      376215.339
     1965813.178      376763.833
#Sta/Elev= 30
       0 1912.42    19.8 1895.96    69.4 1847.39    79.4 1839.24    89.3 1836.03
     119 1836.92     129 1835.69   178.5 1824.64   188.5 1820.54   208.3 1804.21
   218.2 1797.25   317.4 1735.33   436.4 1665.74   476.1 1639.76   505.9 1623.66
   515.8 1619.55   525.7 1617.29     538 1616.61   545.5 1616.53     553 1616.73
   645.3 1624.41   665.2 1627.42   705.1 1640.63   735.1 1652.84     765 1659.47
     775 1662.89   854.8 1706.55   914.6  1729.3   974.4 1753.98  1094.2 1815.32
#Mann= 3 , 0 , 0
       0      .1       0     538    .045       0     553      .1       0
Bank Sta=538,553
XS Rating Curve= 0 ,0
Exp/Cntr=0.3,0.1

Type RM Length L Ch R = 1 ,8169.5  ,261.8,263.8,267.6
XS GIS Cut Line= 3
     1965391.602      375721.649     1965505.119      376255.178
     1965660.178      376781.817
#Sta/Elev= 30
       0 1914.02    49.6 1886.61    59.5 1879.41    79.3 1859.44     119 1815.19
   128.9 1809.21   138.8 1808.78   178.5 1815.29   188.4 1814.96     238 1799.87
   257.9 1787.06   297.5 1755.05   376.9 1695.76   436.4 1654.65   495.9 1620.63
     538 1610.03     553 1608.38   555.4 1608.25   645.3 1616.26   665.2 1621.91
   735.1 1649.38   765.1 1655.93     775 1659.72     785 1666.34     825 1697.96
   854.9 1715.35   934.8 1749.31  1004.6 1782.47  1064.5 1806.25  1094.5 1813.78
#Mann= 3 , 0 , 0
       0      .1       0     538    .045       0     553      .1       0
Bank Sta=538,553
XS Rating Curve= 0 ,0
Exp/Cntr=0.3,0.1

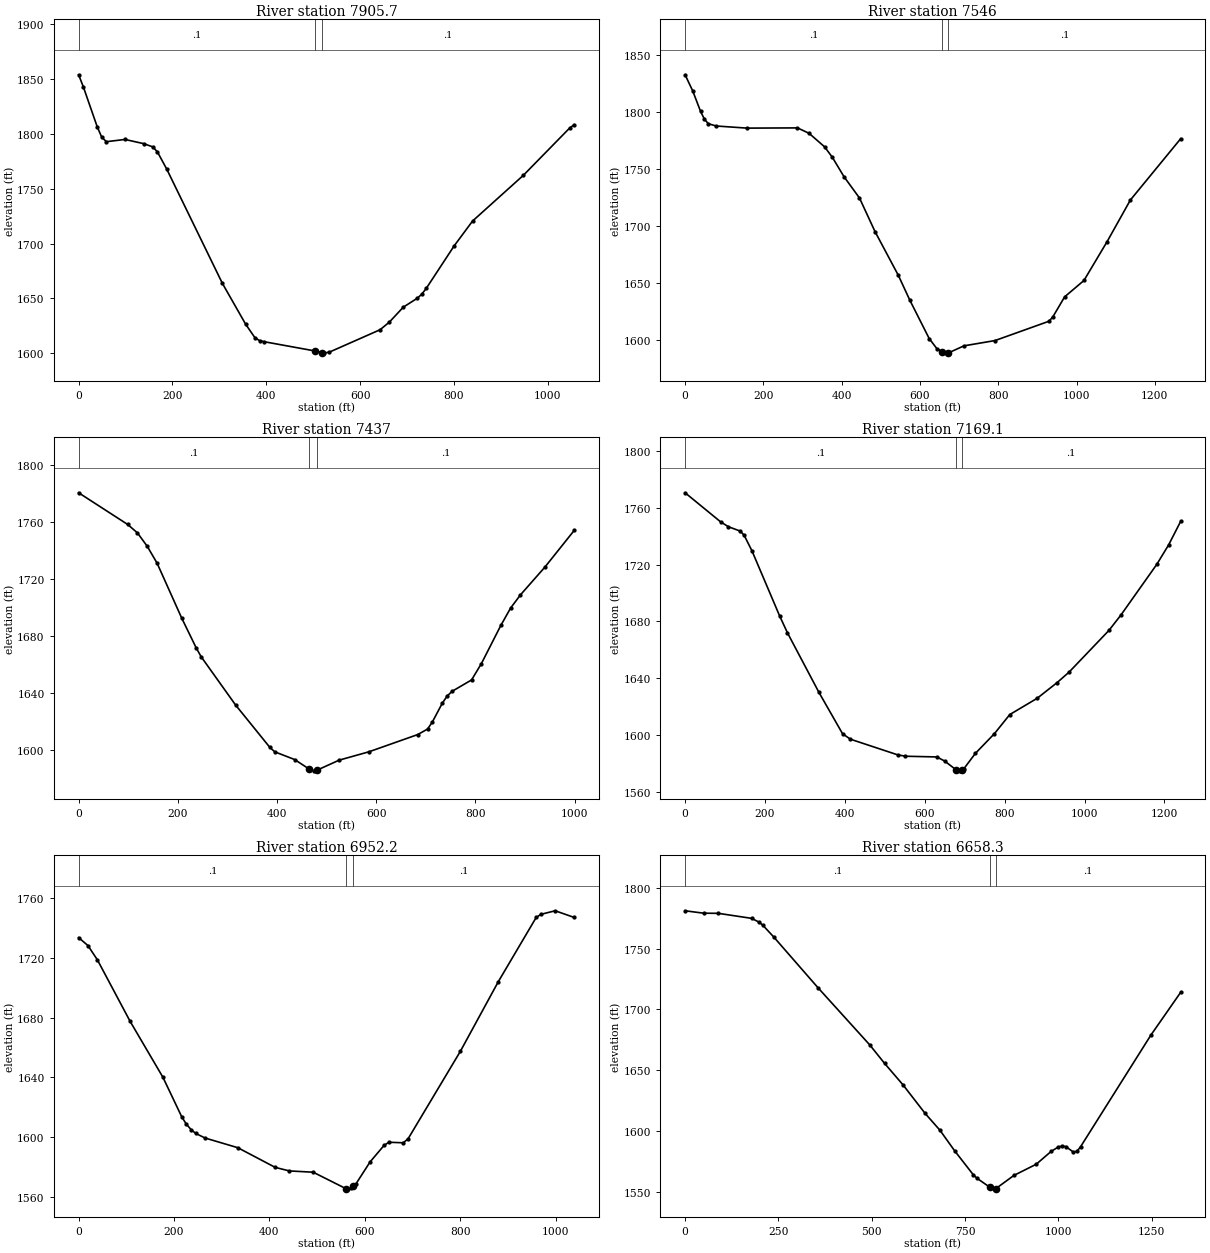
Type RM Length L Ch R = 1 ,7905.7  ,374.1,359.7,345.3
XS GIS Cut Line= 3
     1965207.856      375860.173     1965293.379      376566.752
     1965465.927      376864.745
#Sta/Elev= 30
       0 1853.99     9.9 1843.13    39.5 1806.67    49.4 1796.86    59.3 1792.94
    98.8 1794.98   138.4 1791.17   158.2 1788.17     168 1783.56   187.8  1767.9
   306.4 1663.63   355.9 1626.42   375.6 1614.15   385.5 1611.43   395.4 1610.42
   504.6 1601.91   519.6 1600.52   523.9 1600.27   533.8 1600.82   642.5 1621.36
   662.3 1628.34     692 1641.97   721.6 1650.05   731.4  1653.8   741.2 1659.29
   800.3 1697.86   839.6 1720.56   947.9 1762.29  1046.2 1805.28  1056.1 1808.46
#Mann= 3 , 0 , 0
       0      .1       0   504.6    .045       0   519.6      .1       0
Bank Sta=504.6,519.6
XS Rating Curve= 0 ,0
Exp/Cntr=0.3,0.1

Type RM Length L Ch R = 1 ,7546    ,116.8,109,101.1
XS GIS Cut Line= 3
     1965025.804      375770.286     1964908.527       376302.04
     1965413.518      376817.211
#Sta/Elev= 30
       0 1832.75    19.8 1818.34    39.6 1800.54    49.5 1793.68    59.4 1789.82
    79.2  1787.8   158.4 1785.93   287.1 1786.13   316.8 1781.35   356.4 1769.48
   376.2  1760.3   405.9 1743.31   445.5 1724.59   485.1 1695.16   544.5 1656.87
   574.2 1634.83   623.6 1601.21   643.4 1592.28   656.7 1589.78   671.7 1588.73
     673 1588.69   712.5 1594.84   791.6 1599.46   929.9 1616.46   939.8 1620.45
   969.5 1637.81  1018.9 1652.19  1078.2 1686.39  1137.5 1722.83  1265.9  1776.6
#Mann= 3 , 0 , 0
       0      .1       0   656.7    .045       0   671.7      .1       0
Bank Sta=656.7,671.7
XS Rating Curve= 0 ,0
Exp/Cntr=0.3,0.1

Type RM Length L Ch R = 1 ,7437    ,255.7,267.9,280.1
XS GIS Cut Line= 4
     1964913.045      376058.061      1964877.92      376452.075
     1965047.743      376536.987     1965343.713      376826.237
#Sta/Elev= 30
       0  1780.4    98.9 1758.22   118.7 1752.29   138.4 1742.91   158.2 1731.13
   207.7 1692.79   237.4  1671.6   247.2 1665.55   316.5 1631.84   385.7 1602.12
   395.6 1599.04   435.6 1593.66   465.1 1586.95   475.5 1585.75   480.1 1586.12
   525.5 1593.25   585.4 1599.08     684 1611.16   703.7 1615.02   713.5 1620.06
   733.2    1633   743.1 1638.07     753  1641.4   792.4 1649.39   812.1 1660.76
   851.5  1687.6   871.2 1699.75   890.9  1708.9   940.2 1728.34   999.3 1754.02
#Mann= 3 , 0 , 0
       0      .1       0   465.1    .045       0   480.1      .1       0
Bank Sta=465.1,480.1
XS Rating Curve= 0 ,0
Exp/Cntr=0.3,0.1

Type RM Length L Ch R = 1 ,7169.1  ,187.3,216.9,246.4
XS GIS Cut Line= 5
     1964882.501      376059.588     1964830.744      376549.575
     1964851.894      376714.932     1964951.289      376867.439
     1965256.726      377124.007
#Sta/Elev= 30
       0 1770.55    88.7 1750.14   108.4 1746.64     138 1743.59   147.8 1740.64
   167.5  1729.6   236.5 1683.95   256.2 1671.98     335 1630.05   394.2 1600.91
   413.9 1597.08   531.9  1586.1   551.6  1585.1     630  1584.6   649.6 1581.74
   677.7 1575.66   688.2 1574.82   692.7  1575.5   697.7 1576.26   726.5 1587.07
   774.4 1601.03   812.7 1614.43   881.3 1625.89   931.2 1636.93   961.1  1644.3
  1060.8 1673.63  1090.8 1684.44  1180.5 1720.08  1210.4 1733.89  1240.4 1750.39
#Mann= 3 , 0 , 0
       0      .1       0   677.7    .045       0   692.7      .1       0
Bank Sta=677.7,692.7
XS Rating Curve= 0 ,0
Exp/Cntr=0.3,0.1

Type RM Length L Ch R = 1 ,6952.2  ,287.5,293.9,300.2
XS GIS Cut Line= 3
     1964847.376      376203.144     1964768.026      376617.659
     1964359.911      377080.241
#Sta/Elev= 30
       0 1733.67    19.6 1728.29    39.3 1718.77     108  1677.5   176.7 1640.06
   215.9 1613.73   225.7 1608.65   235.6 1605.05   245.4 1602.43     265 1599.35
   333.7 1592.85   412.2 1579.65   441.9 1577.28   491.7 1576.43   560.9 1565.33
   561.3 1565.28   571.3 1565.58   575.9 1566.94   581.2 1568.51   611.1 1583.36
   640.9 1594.61   650.9  1596.5   680.7 1596.14   690.7 1598.82   800.1 1657.34
   879.7 1704.04   959.3 1747.18   969.3 1749.27   999.1 1751.64  1038.9 1747.18
#Mann= 3 , 0 , 0
       0      .1       0   560.9    .045       0   575.9      .1       0
Bank Sta=560.9,575.9
XS Rating Curve= 0 ,0
Exp/Cntr=0.3,0.1

Type RM Length L Ch R = 1 ,6658.3  ,292,297.9,303.8
XS GIS Cut Line= 3
     1964909.877      375753.955     1964660.104      376389.598
     1964117.831      376738.991
#Sta/Elev= 30
       0 1781.21    49.5 1779.23    89.1  1779.1   178.2 1774.98     198  1771.9
   207.9 1769.45   237.6 1759.63   356.3 1717.83   494.9 1670.82   534.5 1655.67
     584 1637.96   643.4  1614.4     683 1600.61   722.6 1583.59   772.3 1563.99
   782.2  1561.1   817.5 1553.53   831.8  1552.4   832.5 1552.52   881.4 1563.48
     941 1572.64   980.7 1583.13  1000.5 1586.93  1010.5 1587.57  1020.4 1587.16
  1040.2 1582.73  1050.2 1583.25  1060.1 1587.16  1248.6 1679.06    1328 1714.06
#Mann= 3 , 0 , 0
       0      .1       0   817.5    .045       0   832.5      .1       0
Bank Sta=817.5,832.5
XS Rating Curve= 0 ,0
Exp/Cntr=0.3,0.1

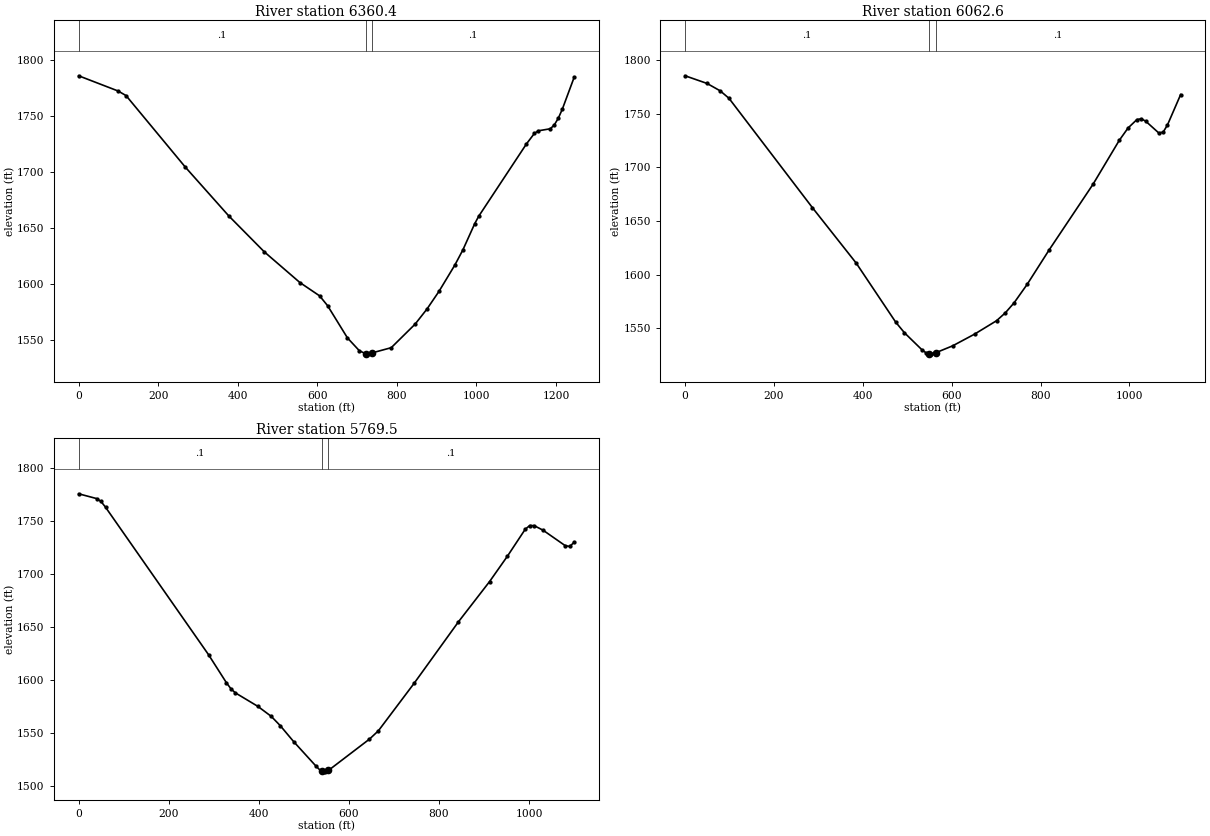
Type RM Length L Ch R = 1 ,6360.4  ,295.9,297.8,299.7
XS GIS Cut Line= 3
     1964859.645      375698.947     1964495.847      376183.258
     1963886.945      376379.725
#Sta/Elev= 30
       0 1785.61    99.3 1772.02   119.2 1767.94   268.1 1704.18   377.3 1660.67
   466.7 1628.59   556.1 1601.23   605.7 1589.34   625.7 1580.61   675.7 1551.82
   705.7 1540.36   721.1 1537.83   725.7 1537.64   736.1 1538.35   785.7 1543.12
   845.7 1564.12   875.6 1577.63   905.6 1593.28   945.6 1616.81   965.6  1630.2
   995.6 1653.77  1005.6 1660.36  1125.6 1724.87  1145.6 1734.24  1155.6 1736.56
  1185.6 1738.35  1195.6 1741.82  1205.6 1747.75  1215.6 1755.72  1245.5 1784.29
#Mann= 3 , 0 , 0
       0      .1       0   721.1    .045       0   736.1      .1       0
Bank Sta=721.1,736.1
XS Rating Curve= 0 ,0
Exp/Cntr=0.3,0.1

Type RM Length L Ch R = 1 ,6062.6  ,294,292.9,286.6
XS GIS Cut Line= 3
     1964835.986      375632.504     1964439.616      375909.923
      1963824.48      376052.851
#Sta/Elev= 30
       0 1785.24    49.4 1778.11      79 1771.22    98.7 1764.31   286.3  1662.6
   385.1 1610.85   473.9 1555.96   493.7 1545.99   533.2  1530.1     543  1527.1
   548.9 1526.67   552.9 1526.38   563.9 1527.35   602.2 1533.83   651.6 1544.75
   700.9 1557.19   720.6 1564.49   740.4 1573.84     770 1591.13   819.3  1623.1
     918 1684.18   977.2 1725.14   996.9 1736.61  1016.7  1744.4  1026.5  1745.2
  1036.4 1743.06    1066 1732.05  1075.9 1732.71  1085.7  1739.5  1115.3 1767.73
#Mann= 3 , 0 , 0
       0      .1       0   548.9    .045       0   563.9      .1       0
Bank Sta=548.9,563.9
XS Rating Curve= 0 ,0
Exp/Cntr=0.3,0.1

Type RM Length L Ch R = 1 ,5769.5  ,348.9,343,342.4
XS GIS Cut Line= 3
     1964783.202      375508.864     1964256.588      375657.026
     1963773.309       375926.46
#Sta/Elev= 30
       0 1775.55    39.8 1771.05    49.7 1768.29    59.7 1762.91   288.4 1623.91
   328.2 1597.42   338.2 1591.74   348.1 1587.87   397.9 1575.18   427.7 1565.74
   447.6 1557.04   477.4 1541.97   527.2 1518.78   537.1  1514.6   539.6 1514.31
   547.1 1513.44   554.6 1514.74   645.9 1544.31   665.6 1552.11   744.7 1596.73
   843.5 1654.91   912.6 1692.83   952.2 1716.74   991.7  1742.1  1001.6 1745.56
  1011.4 1745.54  1031.2 1741.24  1080.6 1726.62  1090.5  1725.9  1100.4 1729.87
#Mann= 3 , 0 , 0
       0      .1       0   539.6    .045       0   554.6      .1       0
Bank Sta=539.6,554.6
XS Rating Curve= 0 ,0
Exp/Cntr=0.3,0.1