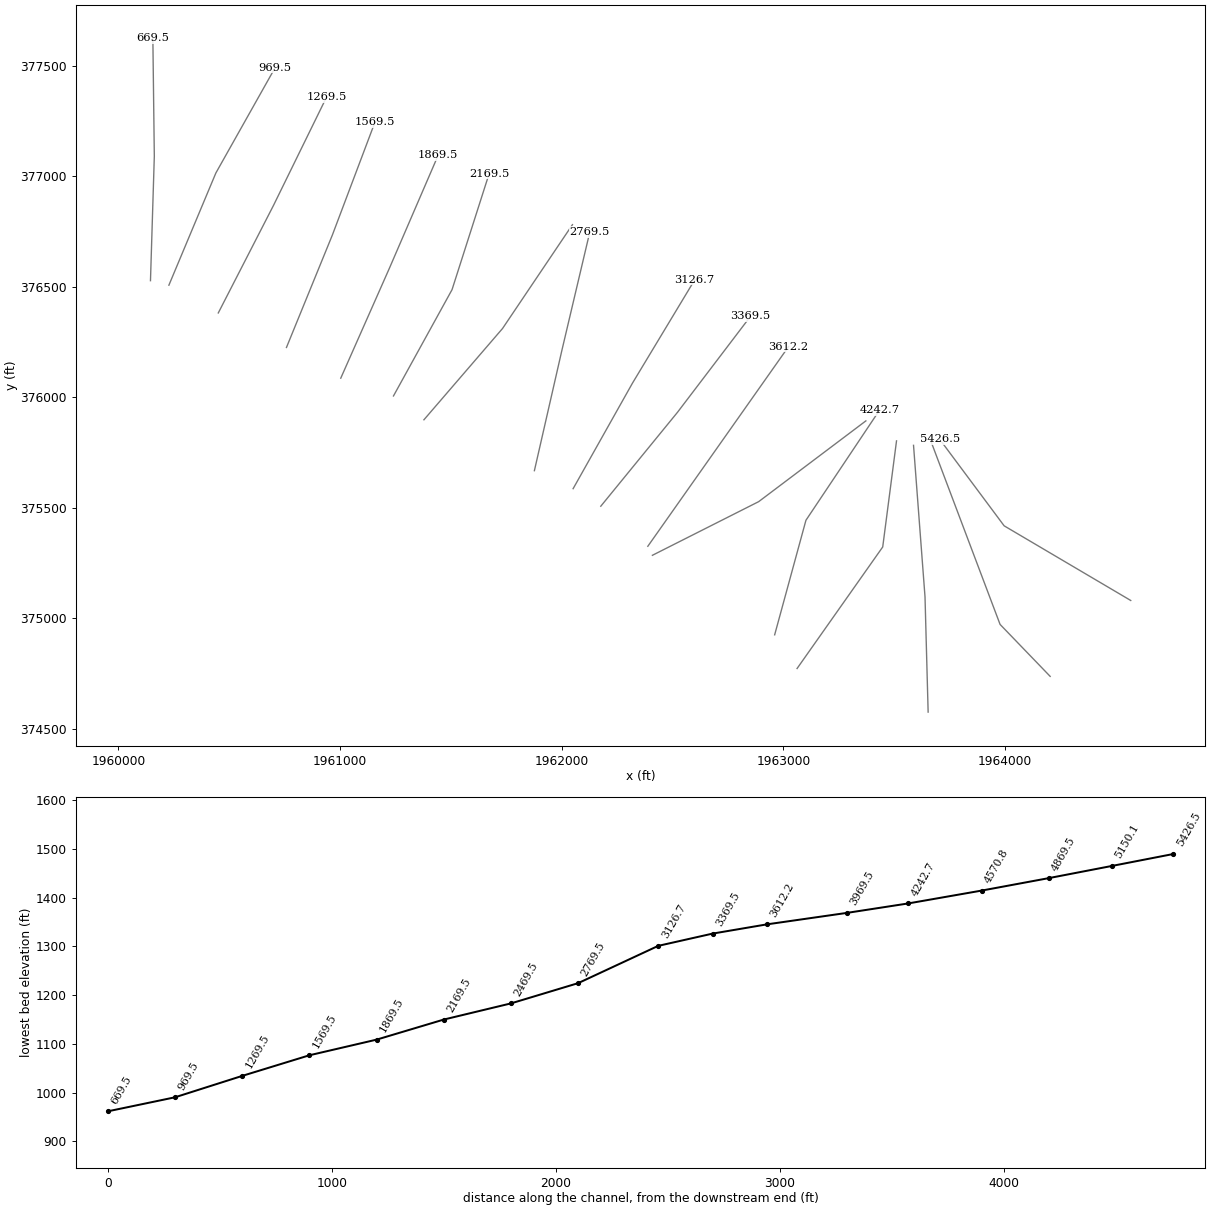
HEC-RAS study KeeneyCrk.prj: KeeneyCrk

--- KeeneyCrk.g01 (geometry) --- (continued)

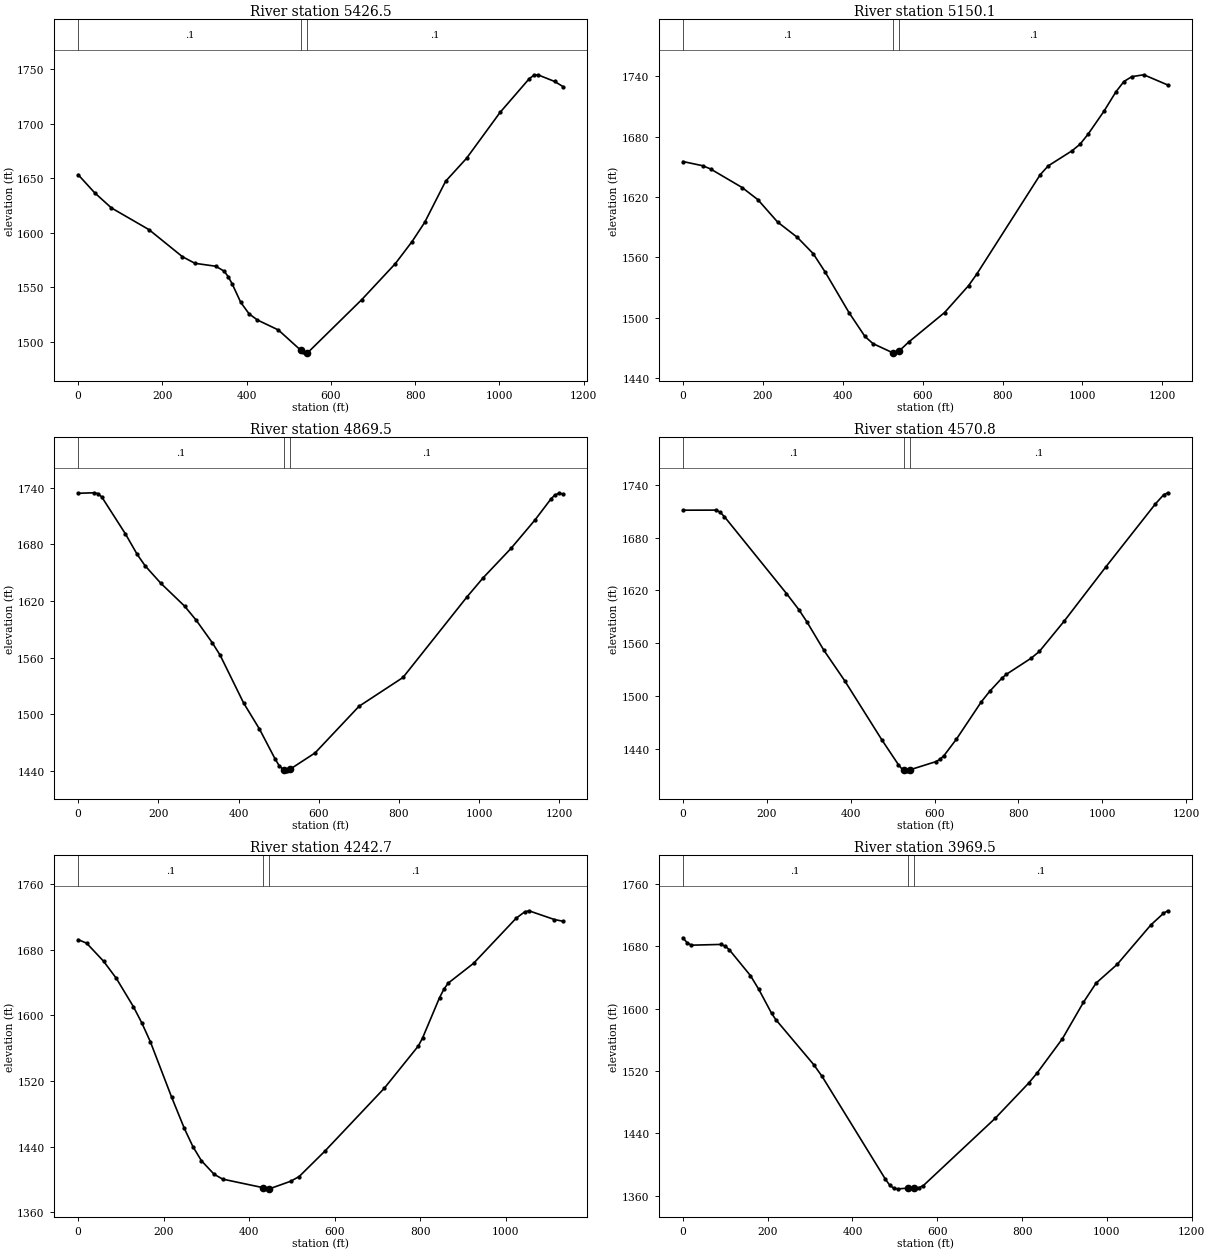
Type RM Length L Ch R = 1 ,5426.5  ,291.8,276.4,261
XS GIS Cut Line= 3
     1964566.759      375081.293     1963995.607      375418.985
      1963704.94      375810.378
#Sta/Elev= 30
       0  1653.2    39.6 1636.47    79.2 1622.66   168.4 1602.76   247.6 1578.02
   277.3 1571.94   326.8 1569.26   346.6 1564.77   356.5 1559.67   366.4 1552.58
   386.2 1536.09     406  1525.6   425.8 1519.98   475.4 1510.86   529.2 1492.07
   534.8 1490.27   544.2 1489.92   544.7  1489.9   673.5  1538.7   753.1 1571.65
   792.9 1591.91   822.7 1609.39   872.4  1647.1   922.2 1668.19  1001.8 1710.24
  1071.4 1741.28  1081.4 1744.06  1091.3  1744.7  1131.1  1738.6    1151 1733.92
#Mann= 3 , 0 , 0
       0      .1       0   529.2    .045       0   544.2      .1       0
Bank Sta=529.2,544.2
XS Rating Curve= 0 ,0
Exp/Cntr=0.3,0.1

Type RM Length L Ch R = 1 ,5150.1  ,288,280.6,274.2
XS GIS Cut Line= 3
     1964203.281       374737.96     1963977.281      374973.046
     1963664.605      375803.489
#Sta/Elev= 30
       0 1655.35    49.4 1651.19    69.2 1647.98   148.2 1629.52   187.8 1617.41
   237.2 1595.15   286.6 1579.93   326.1  1563.8     356 1545.58   415.8 1505.16
   455.7 1481.45   475.6  1474.4   525.5 1465.18   526.4 1465.21   541.4 1467.07
   565.4 1475.98   655.1 1505.27   714.9 1531.94   734.9 1543.07   894.4 1642.28
   914.4 1651.03   974.2 1666.09   994.1  1672.6    1014 1682.45  1053.9 1705.34
  1083.8 1724.63  1103.8 1734.87  1123.7 1739.74  1153.6 1741.58  1213.5 1731.44
#Mann= 3 , 0 , 0
       0      .1       0   526.4    .045       0   541.4      .1       0
Bank Sta=526.4,541.4
XS Rating Curve= 0 ,0
Exp/Cntr=0.3,0.1

Type RM Length L Ch R = 1 ,4869.5  ,313.2,298.8,283.3
XS GIS Cut Line= 3
     1963652.785      374576.388     1963638.709      375097.179
     1963586.879      375782.996
#Sta/Elev= 30
       0 1733.89    39.3 1734.42    49.2 1733.58      59 1730.01     118 1690.94
   147.4  1669.2   167.1 1657.18   206.4 1638.63   265.4 1614.57   294.9 1599.36
   334.2 1576.01   353.9 1562.78   412.8 1511.92   452.2 1484.48   491.5 1452.56
   501.3 1445.73   513.5 1440.82     521 1440.26   528.5 1441.98   590.8 1459.21
   700.4 1508.54     810 1539.02   969.5 1624.22  1009.4 1644.26  1079.2 1675.52
    1139 1705.59  1178.8 1727.85  1188.8 1732.12  1198.8 1733.86  1208.8 1733.24
#Mann= 3 , 0 , 0
       0      .1       0   513.5    .045       0   528.5      .1       0
Bank Sta=513.5,528.5
XS Rating Curve= 0 ,0
Exp/Cntr=0.3,0.1

Type RM Length L Ch R = 1 ,4570.8  ,320.2,328,335.9
XS GIS Cut Line= 3
     1963061.511      374773.537     1963447.856      375323.281
     1963510.154      375803.125
#Sta/Elev= 30
       0  1711.1      79 1711.19    88.9 1708.74    98.8 1703.87     247 1616.36
   276.7 1597.89   296.4 1583.56     336 1551.92   385.4 1517.45   474.3 1449.99
   513.8 1421.76   523.7 1416.04   527.6 1415.54   533.6 1414.76   542.6 1416.13
   602.8 1425.18   612.6 1427.72   622.5 1432.12   652.2 1450.88   711.4  1493.2
   731.2 1505.04   760.8  1520.3   770.7 1524.36   829.9 1542.72   849.7 1550.45
   908.9 1584.92  1007.7 1646.28  1126.2  1718.1  1145.9 1728.54  1155.8  1730.9
#Mann= 3 , 0 , 0
       0      .1       0   527.6    .045       0   542.6      .1       0
Bank Sta=527.6,542.6
XS Rating Curve= 0 ,0
Exp/Cntr=0.3,0.1

Type RM Length L Ch R = 1 ,4242.7  ,292.2,273.4,258.9
XS GIS Cut Line= 3
     1962960.382      374925.894     1963101.498      375444.078
     1963432.589      375940.871
#Sta/Elev= 30
       0 1692.54    19.9 1688.22    59.7 1666.12    89.5 1645.18   129.3 1610.75
   149.2  1590.7   169.1 1567.77   218.8 1500.22   248.6    1462   268.5 1439.93
   288.4 1422.72   318.2 1406.09   338.2  1400.2   432.4 1389.79   447.4 1388.34
   497.3 1397.61   517.2  1403.4   576.9 1434.18   716.2 1511.12   795.8 1562.68
   805.7 1572.43   845.5 1621.76   855.5 1631.84   865.4  1639.3   925.1 1663.62
  1024.6 1718.62  1044.5 1726.37  1054.5 1727.74  1114.2 1717.05  1134.1 1714.96
#Mann= 3 , 0 , 0
       0      .1       0   432.4    .045       0   447.4      .1       0
Bank Sta=432.4,447.4
XS Rating Curve= 0 ,0
Exp/Cntr=0.3,0.1

Type RM Length L Ch R = 1 ,3969.5  ,346.1,356.9,363.3
XS GIS Cut Line= 3
     1962408.855      375285.645     1962888.312      375528.333
     1963371.858      375893.599
#Sta/Elev= 30
       0 1690.87      10 1684.43    19.9  1681.3    89.6 1682.27    99.5 1680.19
   109.5 1675.43   159.2  1642.4   179.1 1624.59     209 1594.13   218.9 1586.02
   308.5 1528.21   328.4 1512.98   477.7 1381.21   487.6 1373.75   497.6 1369.52
   507.5 1368.95   529.9 1369.78   544.9    1370   557.2 1370.63   567.2 1373.18
   736.1 1459.14   815.5 1504.51   835.4 1517.46     895 1561.35   944.7 1608.13
   974.5  1632.7  1024.2  1656.7  1103.6 1707.23  1133.4 1722.14  1143.4  1725.4
#Mann= 3 , 0 , 0
       0      .1       0   529.9    .045       0   544.9      .1       0
Bank Sta=529.9,544.9
XS Rating Curve= 0 ,0
Exp/Cntr=0.3,0.1

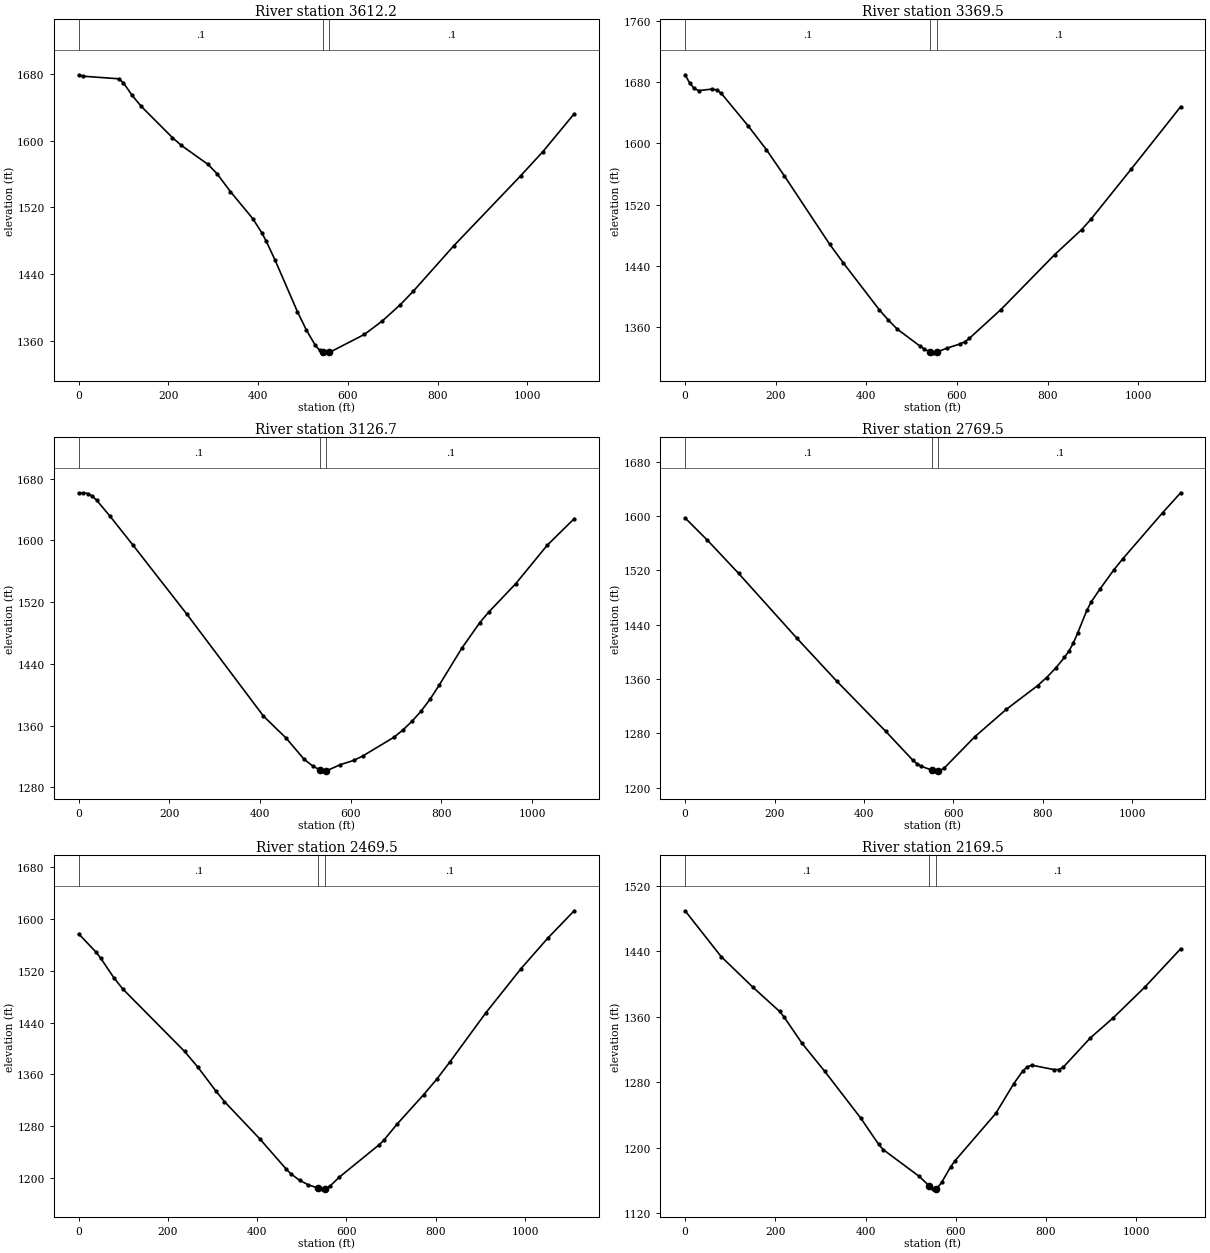
Type RM Length L Ch R = 1 ,3612.2  ,244.1,242.7,242
XS GIS Cut Line= 2
     1962388.204      375326.413     1963023.203      376229.795
#Sta/Elev= 30
       0 1679.37      10 1677.65    89.5 1674.54    99.5 1669.92   119.4 1654.52
   139.3 1641.54   208.9 1603.96   228.8 1594.56   288.5 1571.65   308.4 1560.55
   338.2 1539.12     388 1506.63   407.9 1489.85   417.8  1479.7   437.7 1456.84
   487.4 1395.03   507.4  1372.9   527.2 1354.58   537.2 1348.41     544 1346.36
   547.1 1345.42     559 1345.99   636.7 1367.51   676.5 1383.64   716.3 1402.98
   746.1 1419.66   835.6  1473.8   984.8 1557.98  1034.6 1587.13  1104.2 1632.54
#Mann= 3 , 0 , 0
       0      .1       0     544    .045       0     559      .1       0
Bank Sta=544,559
XS Rating Curve= 0 ,0
Exp/Cntr=0.3,0.1

Type RM Length L Ch R = 1 ,3369.5  ,238.9,242.7,245.4
XS GIS Cut Line= 3
      1962176.02      375507.674     1962522.076      375932.509
     1962851.863       376367.23
#Sta/Elev= 30
       0 1689.41      10 1678.79    19.9 1671.65    29.9 1668.77    59.8 1670.78
    69.7 1669.58    79.7 1665.28   139.5 1622.46   179.3 1591.76   219.2 1557.33
   318.8 1468.39   348.7 1444.17   428.4 1382.76   448.3 1369.29   468.2 1357.39
     518 1335.42     528 1331.42   540.4 1327.65   547.9 1326.42   555.4 1327.32
   577.7 1332.53   607.5 1338.16   617.4 1340.97   627.3  1345.3   696.8 1382.84
   815.8 1454.69   875.3 1487.41   895.2 1500.52   984.5 1566.29  1093.6 1647.71
#Mann= 3 , 0 , 0
       0      .1       0   540.4    .045       0   555.4      .1       0
Bank Sta=540.4,555.4
XS Rating Curve= 0 ,0
Exp/Cntr=0.3,0.1

Type RM Length L Ch R = 1 ,3126.7  ,350.9,357.4,364.2
XS GIS Cut Line= 3
     1962051.179      375586.969     1962318.621      376063.845
     1962599.783      376531.724
#Sta/Elev= 30
       0 1661.43     9.9 1661.89    19.9 1660.93    29.8  1657.6    39.8  1652.2
    69.6  1631.2   119.3 1594.39   238.6 1504.46   407.6 1372.21   457.3 1343.84
     497  1316.3   516.9 1307.19   531.5 1302.68   536.8 1301.39   546.5 1301.25
   576.5 1309.19   606.3 1314.73   626.2 1320.41   695.6 1344.96   715.5  1354.5
   735.3 1365.68   755.2 1378.76     775 1394.26   794.9 1412.32   844.5    1460
   884.2 1493.22     904 1507.02   963.6 1543.87  1033.1  1593.8  1092.6 1628.23
#Mann= 3 , 0 , 0
       0      .1       0   531.5    .045       0   546.5      .1       0
Bank Sta=531.5,546.5
XS Rating Curve= 0 ,0
Exp/Cntr=0.3,0.1

Type RM Length L Ch R = 1 ,2769.5  ,310.5,299.6,291.5
XS GIS Cut Line= 3
     1961876.451      375668.393     1962000.542      376212.844
     1962126.408      376747.687
#Sta/Elev= 30
       0 1597.47    49.9 1564.64   119.7 1515.66   249.3 1420.62     339 1356.91
   448.7 1282.83   508.6 1240.74   518.5 1235.12   528.5 1231.29   550.9 1225.94
   558.4  1224.7   565.9 1224.88   568.4 1224.94   578.4 1228.15   648.3 1275.29
   718.2  1315.4   788.2 1350.31   808.2 1362.18   828.2 1375.92   848.1 1391.86
   858.1 1401.25   868.1 1413.14   878.1 1428.44   898.1 1461.16   908.1 1473.86
     928 1493.08     958  1520.4     978 1536.82  1067.9 1605.35  1107.9 1634.53
#Mann= 3 , 0 , 0
       0      .1       0   550.9    .045       0   565.9      .1       0
Bank Sta=550.9,565.9
XS Rating Curve= 0 ,0
Exp/Cntr=0.3,0.1

Type RM Length L Ch R = 1 ,2469.5  ,295.2,300,306.5
XS GIS Cut Line= 3
     1961378.123       375898.61     1961732.805      376311.559
     1962048.185      376781.277
#Sta/Elev= 30
       0 1577.21    39.6 1548.42    49.5 1539.51    79.2 1509.01      99 1491.94
   237.5 1395.36   267.2 1371.09   306.8 1334.93   326.6 1318.02   405.8  1260.4
   465.2 1213.52   475.1 1206.62   494.9 1196.38   514.7 1189.26   536.9 1184.25
   544.4 1183.16   551.9 1183.41   554.3 1183.49   564.2  1188.2   584.1 1201.33
   673.4 1251.36   683.3 1257.94   713.1 1282.95   772.6 1328.39   802.4  1352.7
   832.2  1379.7   911.6 1454.59     991 1523.35  1050.6 1570.24  1110.1 1612.78
#Mann= 3 , 0 , 0
       0      .1       0   536.9    .045       0   551.9      .1       0
Bank Sta=536.9,551.9
XS Rating Curve= 0 ,0
Exp/Cntr=0.3,0.1

Type RM Length L Ch R = 1 ,2169.5  ,297.9,299.8,297.6
XS GIS Cut Line= 3
     1961240.736      376006.353     1961504.976      376487.214
     1961672.077      377011.153
#Sta/Elev= 30
       0  1489.2    79.8  1433.4   149.6 1396.31   209.5  1366.4   219.5 1359.56
   259.4 1327.37   309.3  1293.5   389.1 1236.49     429 1204.36   438.9 1197.93
   518.8 1165.25   541.2 1153.59   548.7 1149.96   556.2 1150.31   558.7 1150.43
   568.7  1157.8   588.7 1176.79   598.7  1184.4   688.7 1241.94   728.7 1278.31
   748.7 1293.86   758.7 1298.86   768.7 1300.79   818.6 1295.37   828.6 1295.53
   838.6  1298.5   898.6 1334.19   948.6 1358.29  1018.6  1395.7  1098.6  1442.8
#Mann= 3 , 0 , 0
       0      .1       0   541.2    .045       0   556.2      .1       0
Bank Sta=541.2,556.2
XS Rating Curve= 0 ,0
Exp/Cntr=0.3,0.1

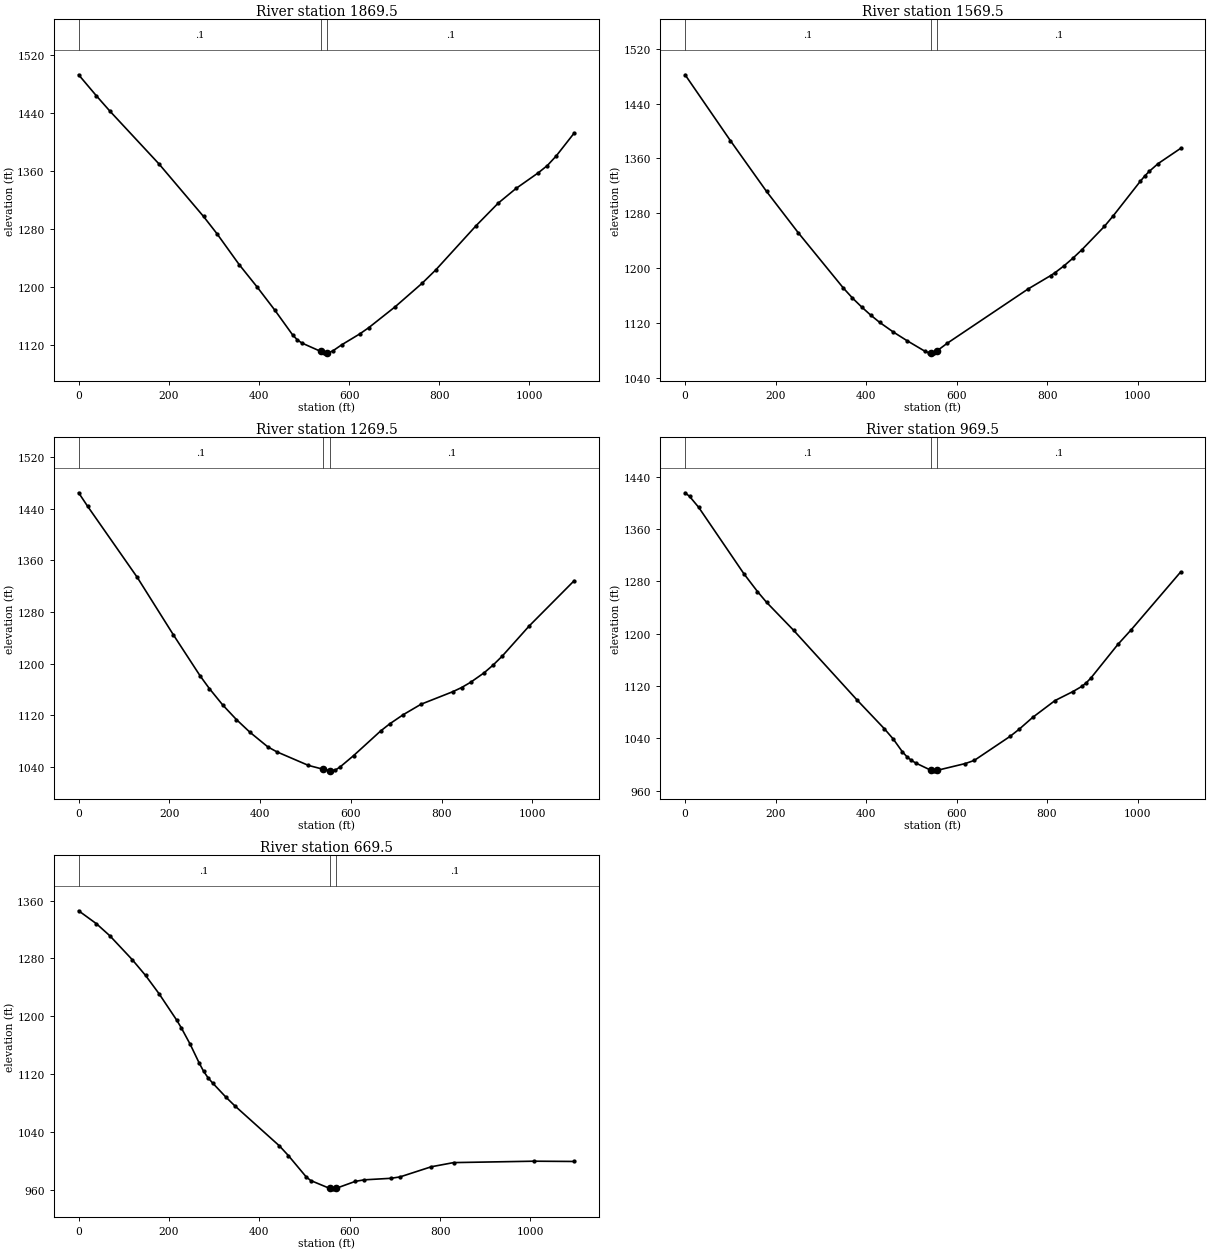
Type RM Length L Ch R = 1 ,1869.5  ,299.3,300,301.1
XS GIS Cut Line= 3
      1961002.94      376086.791     1961222.677      376584.828
     1961442.077      377094.522
#Sta/Elev= 30
       0 1492.43    39.6 1463.27    69.3 1442.33   178.2 1369.45   277.1 1296.91
   306.8 1273.22   356.3 1230.38   395.9 1199.66   435.5 1167.43   475.1 1133.16
     485 1126.77   494.9 1122.38   536.9 1110.76   544.4 1108.75   551.9 1108.74
   554.3 1108.74   564.2 1111.57     584 1119.98   623.6 1134.85   643.4 1143.37
   702.9 1172.68   762.4 1204.99   792.1 1223.06   881.3 1283.93   930.8 1315.31
   970.4  1335.6    1020  1357.3  1039.8 1367.21  1059.6 1380.51  1099.3 1412.01
#Mann= 3 , 0 , 0
       0      .1       0   536.9    .045       0   551.9      .1       0
Bank Sta=536.9,551.9
XS Rating Curve= 0 ,0
Exp/Cntr=0.3,0.1

Type RM Length L Ch R = 1 ,1569.5  ,301.9,300,297.8
XS GIS Cut Line= 3
     1960757.979      376225.684     1960965.309      376734.894
     1961157.349      377245.132
#Sta/Elev= 30
       0 1481.88     100 1385.98   179.9 1311.93   249.9 1251.77   349.9 1170.91
   369.9 1156.45   389.9 1143.61   409.8 1131.79   429.8 1121.07   459.8  1107.1
   489.8 1094.59   529.8 1078.99   539.8 1076.62   542.3 1076.73   549.8 1077.07
   557.3  1079.8   579.5 1090.72     758 1169.74   807.5 1189.11   817.4 1193.42
   837.3 1203.43   857.1 1214.65   876.9 1226.96   926.5 1260.89   946.3 1276.52
  1005.8 1326.62  1015.7 1334.34  1025.6  1341.1  1045.4 1352.51    1095 1374.64
#Mann= 3 , 0 , 0
       0      .1       0   542.3    .045       0   557.3      .1       0
Bank Sta=542.3,557.3
XS Rating Curve= 0 ,0
Exp/Cntr=0.3,0.1

Type RM Length L Ch R = 1 ,1269.5  ,298.3,300,298.7
XS GIS Cut Line= 3
     1960450.408      376381.844     1960699.437      376868.182
     1960939.178      377358.751
#Sta/Elev= 30
       0 1464.76    19.9 1443.77   129.2 1333.84   208.6 1245.14   268.2 1180.92
   288.1 1161.74   317.9 1136.05   347.7 1113.76   377.5  1094.1   417.2 1071.31
   437.1 1063.67   506.6 1042.68   538.9 1036.77   553.9 1034.55   556.3 1034.28
   566.2 1035.65   576.2 1040.17     606 1057.76   665.5 1095.83   685.4 1106.84
   715.2 1121.04   754.9 1137.42   824.4 1156.67   844.2 1163.22   864.1 1171.36
   893.8    1186   913.7 1198.03   933.6 1211.74   993.1 1258.46  1092.4 1328.65
#Mann= 3 , 0 , 0
       0      .1       0   538.9    .045       0   553.9      .1       0
Bank Sta=538.9,553.9
XS Rating Curve= 0 ,0
Exp/Cntr=0.3,0.1

Type RM Length L Ch R = 1 ,969.5   ,291.7,300,311.8
XS GIS Cut Line= 3
       1960227.6      376507.431     1960439.529      377014.932
     1960706.317       377490.51
#Sta/Elev= 30
       0 1415.25      10 1409.65      30 1393.03     130 1291.48     160 1264.29
     180 1247.92     240 1204.98     380 1098.66     440 1054.97     460    1039
     480  1019.7     490 1012.09     500 1006.41     510 1002.22   542.5  991.46
     550  990.33   557.5  991.16   619.4 1001.48   639.2 1006.29   718.5  1043.1
   738.4 1053.93   768.1 1071.91   817.7 1097.76   857.3  1111.5   877.2 1119.51
   887.1 1125.15     897 1132.21   956.5 1183.47   986.2 1206.04  1095.3 1294.19
#Mann= 3 , 0 , 0
       0      .1       0   542.5    .045       0   557.5      .1       0
Bank Sta=542.5,557.5
XS Rating Curve= 0 ,0
Exp/Cntr=0.3,0.1

Type RM Length L Ch R = 1 ,669.5   ,677.2,669.5,660.8
XS GIS Cut Line= 3
     1960144.465      376527.737     1960161.819      377090.438
     1960155.236      377624.246
#Sta/Elev= 30
       0 1345.92    39.5 1327.97    69.1 1311.35   118.5 1278.47   148.2 1256.47
   177.8 1231.43   217.3 1194.52   227.2 1184.16   246.9 1161.39   266.7 1135.62
   276.6 1124.03   286.4 1115.09   296.3    1108   325.9 1088.31   345.7 1076.28
   444.4 1020.89   464.2 1007.53   503.7  978.03   513.6  973.02   555.5  962.16
     563  961.51   570.5  962.37   612.4  971.84   632.2  973.96   691.5  976.09
   711.3     978   780.5  992.02   829.9  997.78  1007.8  999.72  1096.8  999.35
#Mann= 3 , 0 , 0
       0      .1       0   555.5    .045       0   570.5      .1       0
Bank Sta=555.5,570.5
XS Rating Curve= 0 ,0
Exp/Cntr=0.3,0.1

Chan Stop Cuts=-1
Use User Specified Reach Order=0
Composite Channel Slope=5